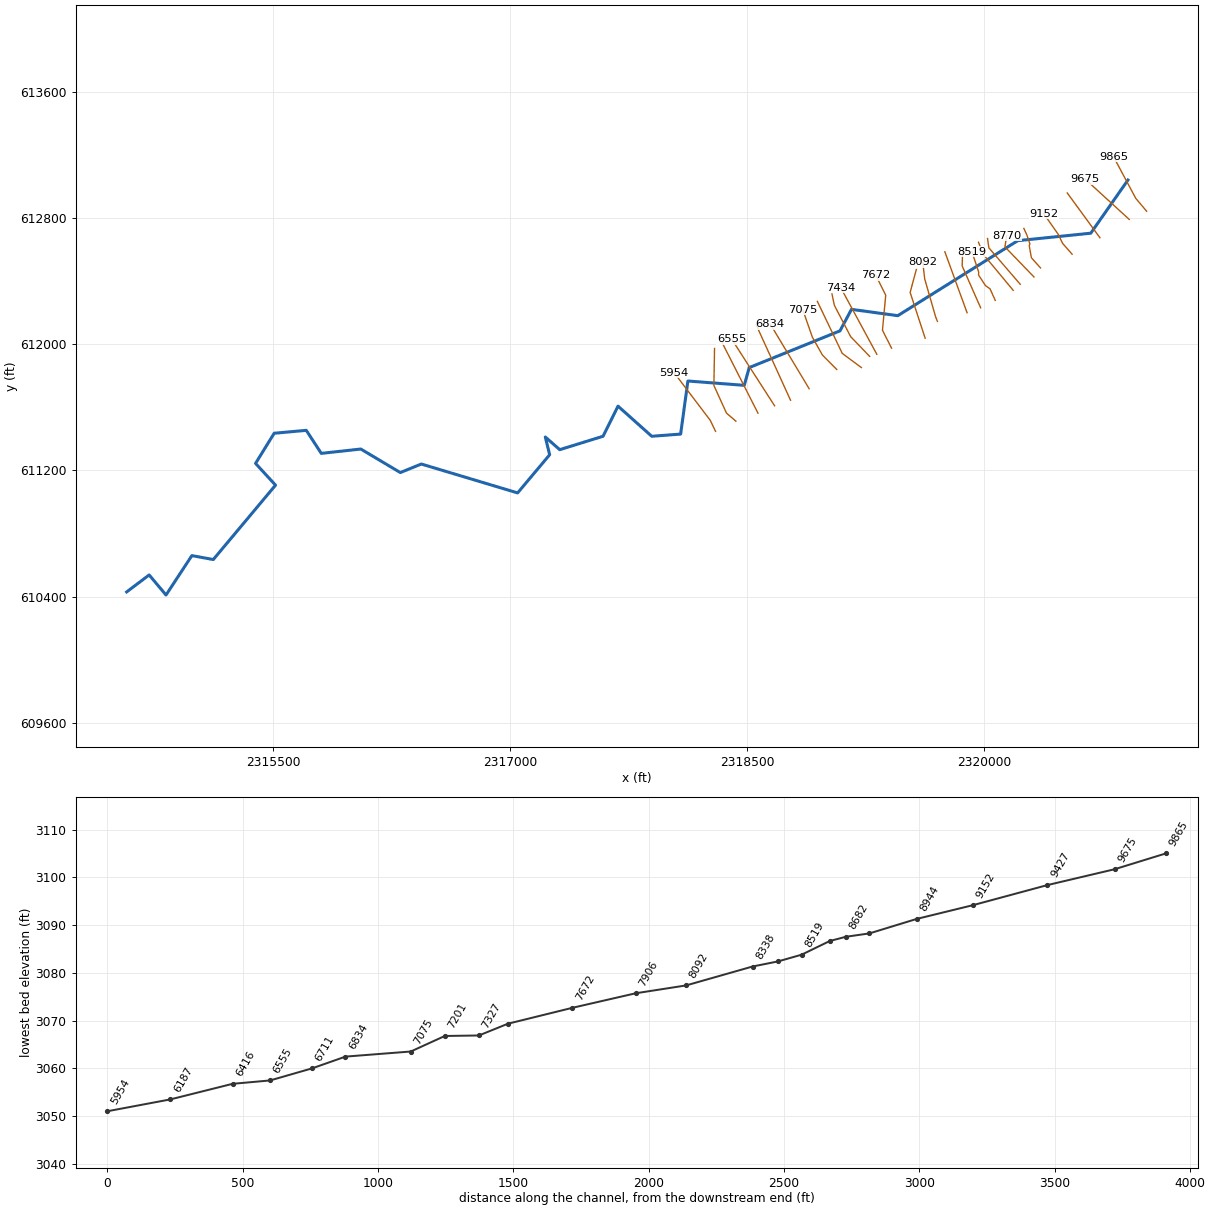
--- ELKLCKRN2.prj (project) ---

Proj Title=ELKLCKRN2
Current Plan=p01
Default Exp/Contr=0,0
English Units
Geom File=g01
Flow File=f01
Plan File=p01
Background Map Layer=Inundation Boundary (01pct Value_0)
BEGIN DESCRIPTION:
----------MODEL BY WOOD PLC 2021----------
Stream Name: Elklick Run II
Flood Zone: Enhanced Approximate
Pocahontas County, WV
HEC-RAS Version: RAS 6.1
Vertical Datum: NAVD88
Projection: NAD 1983 StatePlane West Virginia S FIPS 4702 (US Feet)
Terrain: 1-meter LIDAR (FEMA Region III 3DEP collected 2016-2018)
Land Use: 2019 NLCD
Hydrologic Method:
WV SIR2010-5033 regression equations
END DESCRIPTION:
DSS Export Rating Curves= 0
DSS Export Rating Curve Sorted= 0
DSS Export Volume Flow Curves= 0
DXF OffsetX= 0
DXF OffsetY= 0
DXF ScaleX= 0
DXF ScaleY= 0

--- ELKLCKRN2.p01 (plan) ---

Plan Title=Floodplain
Program Version=6.10
Short Identifier=Floodplain
Geom File=g01
Flow File=f01
Subcritical Flow
K Sum by GR= 0
Std Step Tol= 0.01
Critical Tol= 0.01
Num of Std Step Trials= 20
Max Error Tol= 0.3
Flow Tol Ratio= 0.001
Split Flow NTrial= 30
Split Flow Tol= 0.02
Split Flow Ratio= 0.02
Log Output Level= 0
Friction Slope Method= 1
Unsteady Friction Slope Method= 2
Unsteady Bridges Friction Slope Method= 1
Parabolic Critical Depth
Global Vel Dist= 0 , 0 , 0
Global Log Level= 0
CheckData=True
Encroach Param=-1 ,0,0, 0
Mapping Interval=1HOUR
Computation Time Step Use Courant=        0
Computation Time Step Use Time Series=    0
Computation Time Step Count To Double=0
Computation Time Step Max Doubling=0
Computation Time Step Max Halving=0
Computation Time Step Residence Courant=0
Run HTab= 0
Run UNet= 0
Run Sediment= 0
Run PostProcess= 0
Run WQNet= 0
Run RASMapper=-1
UNET Theta= 0
UNET Theta Warmup= 0
UNET ZTol= 0
UNET ZSATol= 0
UNET MxIter= 0
UNET Max Iter WO Improvement= 0
UNET MaxInSteps= 0
UNET DtIC= 0
UNET DtMin= 0
UNET MaxCRTS= 0
UNET WFStab= 0
UNET SFStab= 0
UNET WFX= 1
UNET SFX= 1
UNET Gravity=32.174
UNET 1D Methodology=Finite Difference
UNET DSS MLevel= 1
UNET Pardiso=0
UNET DZMax Abort= 0
UNET Use Existing IB Tables= 0
UNET Froude Reduction=False
UNET Froude Limit= 0
UNET Froude Power= 0
UNET D1 Cores= 0
UNET WindReference=Eulerian
UNET WindDragFormulation=Hsu (1988)
UNET D2 Coriolis=0
UNET D2 Cores= 0
UNET D2 Theta= 1
UNET D2 Theta Warmup= 1
UNET D2 Z Tol= 0.01
UNET D2 Volume Tol= 0.01
UNET D2 Max Iterations= 20
UNET D2 Equation= 0
UNET D2 RampUpFraction=0.1
UNET D2 TimeSlices= 1
UNET D2 Turbulence Formulation=Non-Conservative (original)
UNET D2 Eddy Viscosity=0.3
UNET D2 Transverse Eddy Viscosity=0.1
UNET D2 Smagorinsky Mixing=0
UNET D2 BCVolumeCheck=0
UNET D2 Cores=0
UNET D2 SolverType=PARDISO (Direct)
UNET D2 Minimum Iterations= 2147483647
UNET D2 Maximum Iterations= 2147483647
UNET D2 Restart Number= 10
UNET D2 Relaxation Coeff=1.3
UNET D2 SOR Precondition Iterations= 10
UNET D2 ILUT Maximum Fill= 8
UNET D2 ILUT Tolerance=1E-08
UNET D1D2 MaxIter= 0
UNET D1D2 ZTol=0.01
UNET D1D2 QTol=0.1
UNET D1D2 MinQTol=1
Write IC File= 0
Write IC File at Fixed DateTime=0
Write IC File at Sim End=0
Echo Input=False
Echo Parameters=False
Echo Output=False
Write Detailed= 0
HDF Write Warmup=0
HDF Write Time Slices=0
HDF Flush=0
HDF Compression= 1
HDF Chunk Size= 1
HDF Spatial Parts= 1
HDF Use Max Rows=0
HDF Fixed Rows= 1
Calibration Method= 0
Calibration Iterations= 20
Calibration Max Change=0.05
Calibration Tolerance=0.2
Calibration Maximum=1.5
Calibration Minimum=0.5
Calibration Optimization Method= 1
WQ AD Non Conservative
WQ ULTIMATE=-1
WQ Max Comp Step=1HOUR
WQ Output Interval=15MIN
WQ Output Selected Increments= 0
WQ Output face flow=0
WQ Output face velocity=0
WQ Output face area=0
WQ Output face dispersion=0
WQ Output cell volume=0
WQ Output cell surface area=0
WQ Output cell continuity=0
WQ Output cumulative cell continuity=0
WQ Output face conc=0
WQ Output face dconc_dx=0
WQ Output face courant=0
WQ Output face peclet=0
WQ Output face adv mass=0
WQ Output face disp mass=0
WQ Output cell mass=0
WQ Output cell source sink temp=0
WQ Output nsm pathways=0
WQ Output nsm derived pathways=0
WQ Create Restart=0
WQ Fixed Restart=0
WQ System Summary=0
WQ Write To DSS=0
Sorting and Armoring Iterations= 10
XS Update Threshold= 0.02
Bed Roughness Predictor= 0
Hydraulics Update Threshold= 0.02
Energy Slope Method= 1
Volume Change Method= 1
Sediment Retention Method= 0
Sediment TS Multiplier= 1
Warm Up Method= 0
XS Weighting Method= 0
Number of US Weighted Cross Sections= 1
Number of DS Weighted Cross Sections= 1
Upstream XS Weight=0
Main XS Weight=1
Downstream XS Weight=0
Number of DS XS's Weighted with US Boundary= 1
Upstream Boundary Weight= 1
Weight of XSs Associated with US Boundary= 0
Number of US XS's Weighted with DS Boundary= 1
Downstream Boundary Weight= 0.5
Weight of XSs Associated with DS Boundary= 0.5
Percentile Method= 0
Sediment Output Level= 3
Mass or Volume Output= 0
Output Increment Type= 1
Profile and TS Output Increment= 1
Transport Output Increment 1
XS Output Flag= 0
XS Output Increment= 10
Read HDF5 Sediment Hotstart= 0
Sediment Hotstart Type= 0
Write Gradation File= 0
Read Gradation Hotstart= 0
Write HDF5 File= 1
Write Binary Output= 1
Write DSS Sediment File= 0
DSS Sediment Output Type= 1
SV Curve= 0
Specific Gage Flag= 0
Subcell Erosion Methods= 0
Subcell Deposition Methods= 0
Advection Scheme= 1
Matrix Solver= 0
Implicit Weighting Factor= 1
Maximum Outer Loop Convergence Iterations= 5
Convergence Maximum Absolute= 0.001
Convergence RMSE= 0.0001
Grain Fractions Max Abs Error= 0.001
Max Subgrid Regions= 1
Max Subgrid Length Scale= 3.402823E+38
Initial Layer Thickness= 3.402823E+38
Min Layer Thickness= 3.402823E+38
Max Layer Thickness= 3.402823E+38
Number of Layers= 5

--- ELKLCKRN2.f01 (steady flow) ---

Flow Title=Flow
Program Version=6.10
Number of Profiles= 6
Profile Names=01pct,10pct,04pct,02pct,0_2pct,01plus
River Rch & RM=ELKLCKRN2,Main            ,9865
     620     329     436     525     865     917
River Rch & RM=ELKLCKRN2,Main            ,6187
     690     367     487     585     960    1020
Boundary for River Rch & Prof#=ELKLCKRN2,Main            , 1
Up Type= 0
Dn Type= 3
Dn Slope=0.02273
Boundary for River Rch & Prof#=ELKLCKRN2,Main            , 2
Up Type= 0
Dn Type= 3
Dn Slope=0.02273
Boundary for River Rch & Prof#=ELKLCKRN2,Main            , 3
Up Type= 0
Dn Type= 3
Dn Slope=0.02273
Boundary for River Rch & Prof#=ELKLCKRN2,Main            , 4
Up Type= 0
Dn Type= 3
Dn Slope=0.02273
Boundary for River Rch & Prof#=ELKLCKRN2,Main            , 5
Up Type= 0
Dn Type= 3
Dn Slope=0.02273
Boundary for River Rch & Prof#=ELKLCKRN2,Main            , 6
Up Type= 0
Dn Type= 3
Dn Slope=0.02273
DSS Import GetInterval= 0
DSS Import GetPeak= 0
DSS Import FillOption= 0

--- ELKLCKRN2.g01 (geometry) ---

Geom Title=Geometry
Program Version=6.10

River Reach=ELKLCKRN2       ,Main
Reach XY= 30
     2320910.451      613039.2632320675.09204947612702.225550694
2320212.95575827612654.823625101     2319453.647      612179.599
     2319160.678      612219.785     2319087.826      612083.482
     2318513.331       611850.67      2318482.09      611738.272
     2318125.168      611765.632     2318079.379      611429.437
     2317896.487      611415.448     2317682.843       611606.45
     2317588.335      611415.578     2317313.979      611330.668
     2317222.762      611410.987     2317250.214      611298.309
     2317047.478       611056.57     2316438.046        611239.6
     2316305.115      611185.5492316054.96499032611334.606495159
     2315804.796      611307.164       2315709.9      611453.122
2315506.81249193611434.639364914     2315388.812      611243.489
     2315515.354      611105.734     2315121.377      610634.468
2314985.71674597610659.392381052     2314822.234      610409.715
      2314715.41      610536.797     2314573.097      610429.222

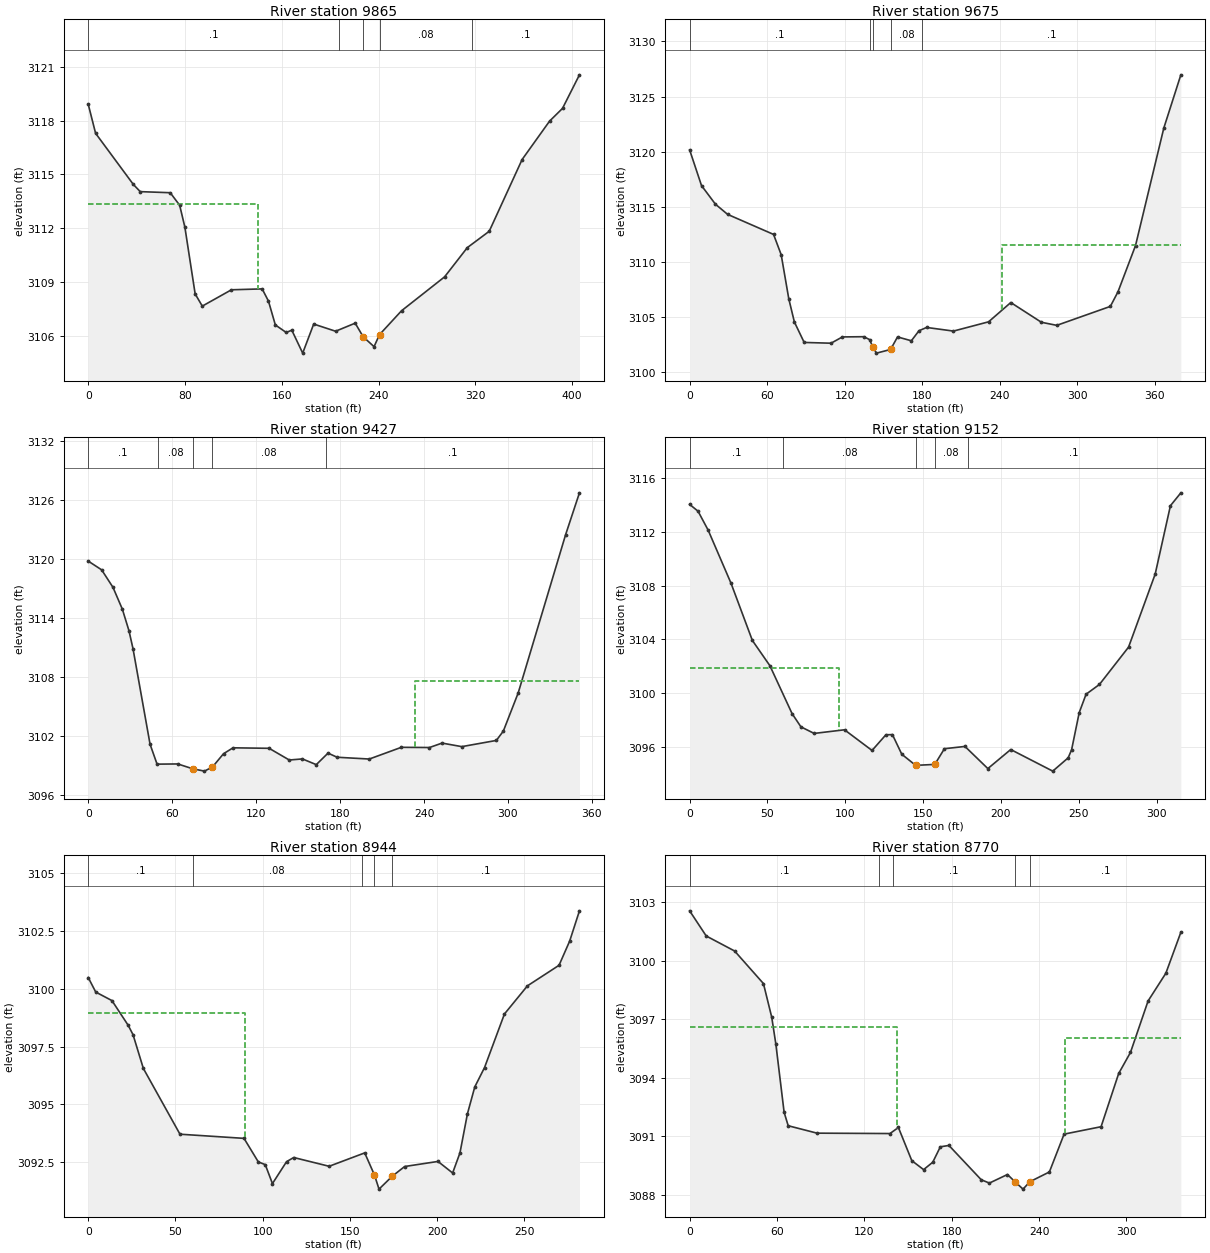
Type RM Length L Ch R = 1 ,9865    ,182.4,189.9,192.2
XS GIS Cut Line= 3
2321028.85970759612841.2799264362320959.92751281612923.199346322
 2320819.0660713 613186.93991766
#Sta/Elev= 30
       0 3118.91     6.1 3117.29    37.3 3114.44      43 3114.04    67.8 3113.98
    75.6 3113.28    79.9 3112.06    88.4 3108.34    94.3 3107.66   118.4 3108.57
   143.8 3108.62     149 3107.94   154.7 3106.61   163.7 3106.19   168.3 3106.32
   177.3 3105.04   186.4 3106.66   204.5 3106.26   220.7 3106.71   227.33105.951
   236.3  3105.4   240.8 3106.07     259  3107.4   294.6 3109.29   313.4 3110.92
   331.5 3111.83   358.7 3115.83   381.4 3117.97   392.1 3118.68   406.1 3120.55
#Mann= 5 ,-1,0
       0      .1       0  207.06     .08       0   227.3    .045       0
   240.8     .08       0  317.06      .1       0
#XS Ineff= 2 , 0
          140.06 3113.36
Permanent Ineff=
       F       F
Bank Sta=227.3,240.8
XS Rating Curve= 0 ,0
Exp/Cntr(USF)=0,0
Exp/Cntr=0.3,0.1

Type RM Length L Ch R = 1 ,9675    ,243.3,247.8,238.5
XS GIS Cut Line= 2
2320918.96780287612789.3310260212320638.24393716 613046.07847615
#Sta/Elev= 30
       0 3120.16     9.2 3116.92      20 3115.23    29.4 3114.31      65 3112.49
    70.9 3110.65    76.8 3106.64    81.1 3104.55    88.7 3102.69   109.5 3102.62
   118.3 3103.19   134.9 3103.21   139.3 3102.95     142 3102.25   144.7 3101.72
   155.6 3102.05     161 3103.19   171.7 3102.84   177.6 3103.75   183.5 3104.05
   204.3 3103.72   231.5 3104.56   248.7 3106.31   272.4 3104.52   284.3 3104.24
   325.8 3105.96   331.7 3107.28   345.3 3111.48   367.2 3122.14   380.4 3126.97
#Mann= 5 ,-1,0
       0      .1       0     140     .08       0     142    .045       0
   155.6     .08       0     180      .1       0
#XS Ineff= 2 , 0
                          241.83         3111.54
Permanent Ineff=
       F       F
Bank Sta=142,155.6
XS Rating Curve= 0 ,0
Exp/Cntr(USF)=0,0
Exp/Cntr=0.3,0.1

Type RM Length L Ch R = 1 ,9427    ,269,275.9,273.4
XS GIS Cut Line= 2
2320733.15058215612673.4450174032320526.35399781612957.165935055
#Sta/Elev= 30
       0 3119.76     9.6 3118.87    17.7 3117.09    24.4 3114.87    29.1 3112.69
      32 3110.86    44.2 3101.14    49.2 3099.12      64 3099.14    74.9 3098.64
    83.1 3098.41    88.8 3098.83    96.7 3100.18   103.5 3100.78   129.3 3100.73
   143.7 3099.54   153.1 3099.65     163 3099.07   171.4 3100.24   177.9 3099.82
   200.9 3099.64   223.8 3100.83   243.9 3100.81   252.9 3101.26     267  3100.9
   291.7 3101.53   296.7 3102.48   307.3 3106.35   341.2 3122.44   351.1  3126.7
#Mann= 5 ,-1,0
       0      .1       0      50     .08       0    74.9    .045       0
    88.8     .08       0     170      .1       0
#XS Ineff= 2 , 0
                          233.86          3107.6
Permanent Ineff=
       F       F
Bank Sta=74.9,88.8
XS Rating Curve= 0 ,0
Exp/Cntr(USF)=0,0
Exp/Cntr=0.3,0.1

Type RM Length L Ch R = 1 ,9152    ,212.1,207.2,201.1
XS GIS Cut Line= 5
2320556.99672178612569.1510200512320496.61893517612638.121048468
2320476.02445819612681.3780440662320467.12658952 612698.13172863
2320376.84400468612826.626472076
#Sta/Elev= 30
       0 3114.07     5.4 3113.56    11.9 3112.15    26.6 3108.19    40.3 3103.93
    51.6 3102.04    65.8 3098.48    71.5 3097.49      80    3097    99.5 3097.27
   117.2 3095.73   126.1  3096.9   130.3 3096.91   136.3 3095.45   145.2 3094.62
   157.5 3094.69   163.7 3095.86   176.9 3096.03   191.6 3094.38   206.3  3095.8
   233.3 3094.19   243.2 3095.18   245.4 3095.78   250.3 3098.55   254.7 3099.92
   263.3 3100.65     282 3103.43   299.1 3108.87   308.9 3113.97   315.6 3114.93
#Mann= 5 ,-1,0
       0      .1       0      60     .08       0   145.2    .045       0
   157.5     .08       0  178.54      .1       0
#XS Ineff= 2 , 0
           96.22 3101.84
Permanent Ineff=
       F       F
Bank Sta=145.2,157.5
XS Rating Curve= 0 ,0
Exp/Cntr(USF)=0,0
Exp/Cntr=0.3,0.1

Type RM Length L Ch R = 1 ,8944    ,162.8,174.5,181.2
XS GIS Cut Line= 6
2320357.20862857 612481.938410242320299.44471653612546.543013573
2320285.59061033612622.4107379982320289.68274287612634.684394811
2320270.52610748612691.3073275372320251.76859236612732.376550157
#Sta/Elev= 30
       0 3100.49     4.3 3099.86    13.6 3099.49    22.9 3098.42    25.7 3098.01
    31.6 3096.55    52.6  3093.7    89.3 3093.52    97.5  3092.5   101.5 3092.38
   105.6 3091.56   113.7 3092.51   117.8 3092.69   138.1 3092.31   158.5 3092.89
   164.1 3091.93   166.7 3091.32   174.3 3091.88   181.4  3092.3   200.5 3092.52
   208.9 3092.02   213.1 3092.89   217.4 3094.59   221.6 3095.75   227.2 3096.59
   238.6 3098.91   251.8 3100.13   269.9 3101.02     276 3102.07   281.6 3103.38
#Mann= 5 ,-1,0
       0      .1       0      60     .08       0  156.66      .1       0
   164.1    .045       0   174.3      .1       0
#XS Ineff= 2 , 0
           89.64 3098.96
Permanent Ineff=
       F       F
Bank Sta=164.1,174.3
XS Rating Curve= 0 ,0
Exp/Cntr(USF)=0,0
Exp/Cntr=0.3,0.1

Type RM Length L Ch R = 1 ,8770    ,87.9,87.9,87.1
XS GIS Cut Line= 3
2320315.67960962612424.9525072732320131.91153576612615.584343768
2320142.64940064612687.398942523
#Sta/Elev= 30
       0 3102.56    11.4 3101.27    30.9  3100.5    50.7 3098.83    56.4  3097.1
    59.2 3095.74    64.9 3092.23    67.7 3091.54    87.5 3091.16   137.6 3091.14
   143.4 3091.45   152.6 3089.75   160.7 3089.29     167 3089.67   172.2 3090.46
   178.1 3090.53   200.3 3088.77   205.9  3088.6   218.3 3089.04   223.3 3088.68
     229 3088.29   233.7 3088.67   247.1 3089.17   257.2 3091.11   282.6 3091.49
   294.7 3094.22   302.8  3095.3   314.9 3097.94   327.1 3099.36   337.4 3101.46
#Mann= 5 ,-1,0
       0      .1       0     130     .08       0     140      .1       0
   223.3    .045       0   233.7      .1       0
#XS Ineff= 2 , 0
          142.23  3096.6  258.13         3096.06
Permanent Ineff=
       F       F
Bank Sta=223.3,233.7
XS Rating Curve= 0 ,0
Exp/Cntr(USF)=0,0
Exp/Cntr=0.3,0.1

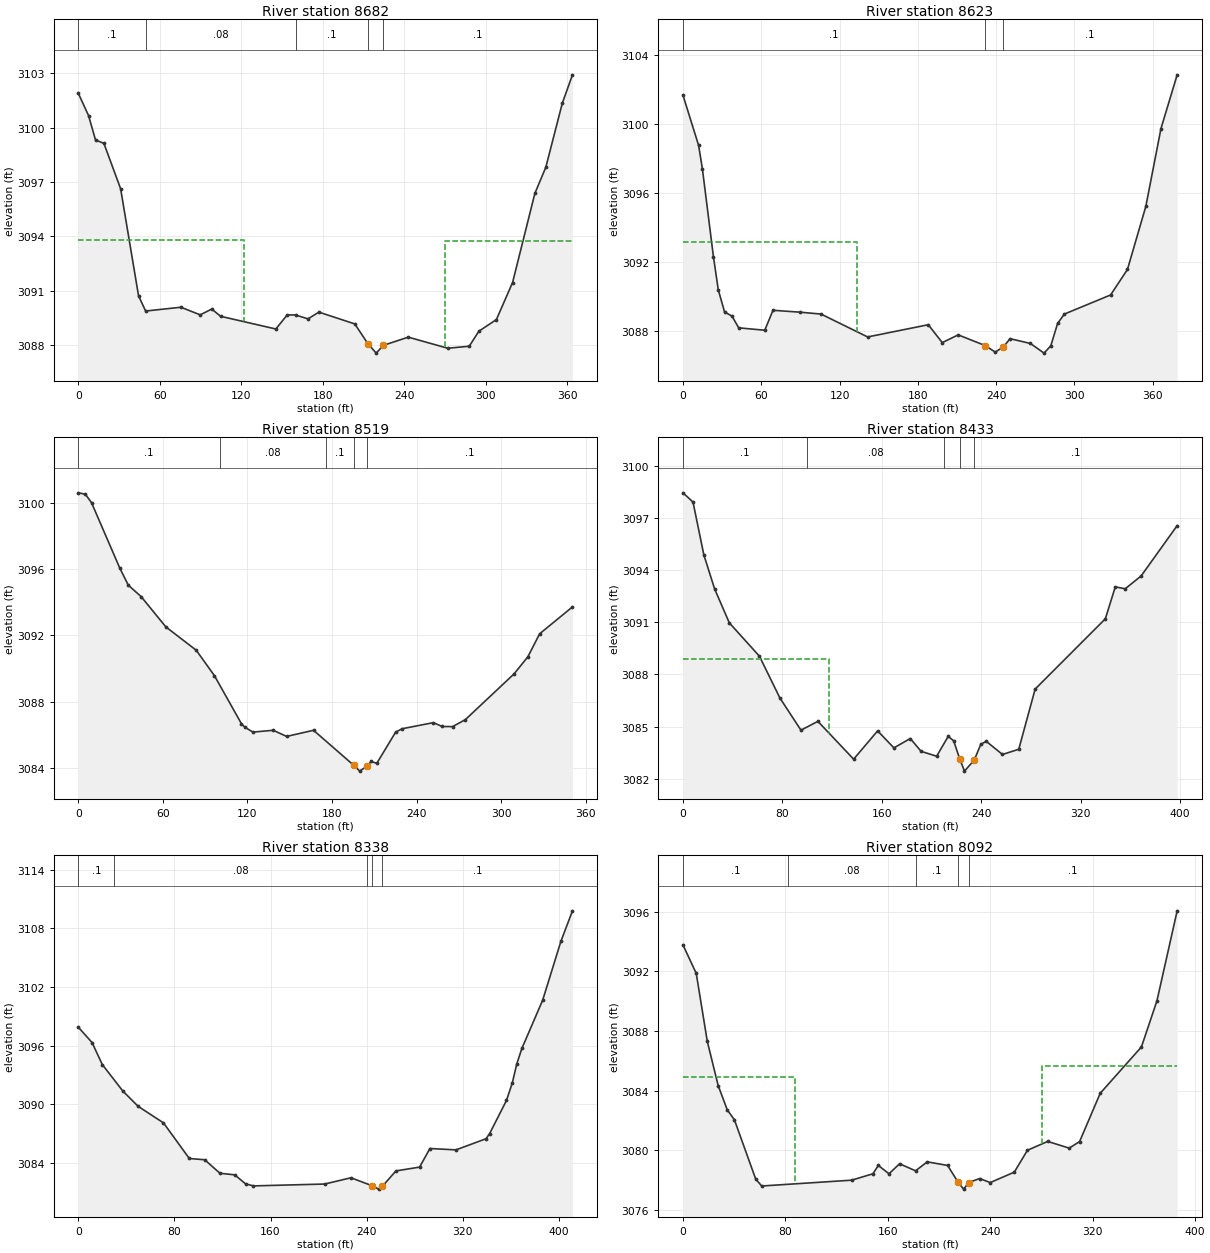
Type RM Length L Ch R = 1 ,8682    ,58.9,59,59.3
XS GIS Cut Line= 3
 2320228.4846352612378.813260228 2320030.2027253612609.498900669
2320021.63758092612668.624974182
#Sta/Elev= 30
       0  3101.9     7.6 3100.66    12.7 3099.32    18.9 3099.13    31.2 3096.63
    44.4 3090.73    49.6 3089.89    75.6  3090.1    89.8 3089.68    98.3    3090
   104.8  3089.6   145.5  3088.9   153.9 3089.68     160 3089.67   169.2 3089.46
   177.2 3089.83   203.6 3089.18   213.33088.088   219.4 3087.57   224.7    3088
     243 3088.45   272.1 3087.84   287.9 3087.95     295 3088.78   307.9 3089.42
   319.8 3091.46   336.2 3096.37   344.3 3097.82   356.4 3101.34   363.9 3102.91
#Mann= 5 ,-1,0
       0      .1       0      50     .08       0     160      .1       0
   213.3    .045       0   224.7      .1       0
#XS Ineff= 2 , 0
          122.38 3093.82  269.89         3093.77
Permanent Ineff=
       F       F
Bank Sta=213.3,224.7
XS Rating Curve= 0 ,0
Exp/Cntr(USF)=0,0
Exp/Cntr=0.3,0.1

Type RM Length L Ch R = 1 ,8623    ,109.5,103.8,98.9
XS GIS Cut Line= 3
2320184.23763251612340.2935949212319993.18950701612570.445137916
2319964.69987426612644.741631165
#Sta/Elev= 30
       0 3101.68      12 3098.76    14.9  3097.4    23.4 3092.27    27.1 3090.36
    31.9 3089.08    37.6 3088.84    42.7 3088.16    62.7 3088.02      69 3089.18
    89.5 3089.07   105.8 3088.96   141.5 3087.63     188 3088.34   198.7  3087.3
   210.9 3087.75   231.73087.127   239.3 3086.75   245.5 3087.05   250.7 3087.53
   266.3 3087.25   276.7 3086.69   281.9 3087.12   287.1 3088.42   292.3 3088.96
   327.7 3090.07   340.6 3091.55   354.7 3095.22   366.3 3099.74   378.7 3102.86
#Mann= 3 ,-1,0
       0      .1       0   231.7    .045       0   245.5      .1       0
#XS Ineff= 2 , 0
          133.33 3093.16
Permanent Ineff=
       F       F
Bank Sta=231.7,245.5
XS Rating Curve= 0 ,0
Exp/Cntr(USF)=0,0
Exp/Cntr=0.3,0.1

Type RM Length L Ch R = 1 ,8519    ,83.5,86.5,91.8
XS GIS Cut Line= 6
2320070.62368286612276.6293245142320037.36541736612349.870646179
2320008.55476619612370.3533886782319964.62558913612437.729000312
2319966.25551888612453.7176286662319923.29814364612584.061013582
#Sta/Elev= 30
       0 3100.59       5 3100.51     9.4    3100    29.5 3096.05    35.5 3095.03
    44.6 3094.34    62.1 3092.52    83.7 3091.11    96.6 3089.58   115.8 3086.68
   118.1 3086.48   123.9 3086.18   138.3 3086.29   147.8 3085.92   166.9 3086.29
   195.6 3084.17   199.7 3083.83   205.1 3084.15   207.7 3084.41   211.8  3084.3
   225.1 3086.17   229.6 3086.38   251.9 3086.75   258.1 3086.52   265.5 3086.51
   274.6 3086.93   309.1 3089.68     319 3090.72   327.3  3092.1   350.6 3093.72
#Mann= 5 ,-1,0
       0      .1       0  100.44     .08       0  175.79      .1       0
   195.6    .045       0   205.1      .1       0
Bank Sta=195.6,205.1
XS Rating Curve= 0 ,0
Exp/Cntr(USF)=0,0
Exp/Cntr=0.3,0.1

Type RM Length L Ch R = 1 ,8433    ,94.6,95,92.9
XS GIS Cut Line= 3
2319977.99082459612229.8038704142319861.21719709612494.686576853
2319864.19833048612602.926786711
#Sta/Elev= 30
       0 3098.47     8.1 3097.94    16.8  3094.9    25.5 3092.93    37.3 3090.98
    61.6 3089.05      78 3086.65      95 3084.79   108.6  3085.3   137.4 3083.12
   156.7 3084.75   169.8 3083.77     183 3084.31   191.7 3083.57   204.2 3083.29
   213.5 3084.43   217.9 3084.18   222.7 3083.15   226.6 3082.43   234.5 3083.07
   239.7 3083.97   244.1 3084.15   257.2 3083.39   270.3 3083.69   283.5 3087.16
     340 3091.21     348 3093.05     356 3092.94   368.8 3093.68   397.8 3096.58
#Mann= 5 ,-1,0
       0      .1       0     100     .08       0     210      .1       0
   222.7    .045       0   234.5      .1       0
#XS Ineff= 2 , 0
          117.87 3088.92
Permanent Ineff=
       F       F
Bank Sta=222.7,234.5
XS Rating Curve= 0 ,0
Exp/Cntr(USF)=0,0
Exp/Cntr=0.3,0.1

Type RM Length L Ch R = 1 ,8338    ,242.7,245.5,243.5
XS GIS Cut Line= 2
2319892.21719396612198.3639942522319751.45885484612584.674388233
#Sta/Elev= 30
       0  3097.9    11.5 3096.32      20 3094.08    37.1 3091.37    49.8 3089.81
    70.9 3088.12    92.4 3084.48   105.2 3084.35   117.9 3082.97   130.2 3082.81
   139.2 3081.89   145.8 3081.68     205 3081.87   226.9 3082.51   244.63081.691
   249.9 3081.35   253.13081.644   264.3 3083.21     284  3083.6   292.6  3085.5
   314.3 3085.36   339.3  3086.5   342.3 3087.03   356.3 3090.41   361.1 3092.18
   364.9 3094.15   369.1 3095.72   386.4 3100.65   401.6 3106.67   411.2 3109.78
#Mann= 5 ,-1,0
       0      .1       0      30     .08       0     240      .1       0
   244.6    .045       0   253.1      .1       0
Bank Sta=244.6,253.1
XS Rating Curve= 0 ,0
Exp/Cntr(USF)=0,0
Exp/Cntr=0.3,0.1

Type RM Length L Ch R = 1 ,8092    ,187.1,185.9,180.5
XS GIS Cut Line= 4
2319704.48853683612143.5021165872319692.85012772612173.505390868
2319623.95674935612412.5394557032319612.12365282612516.892213011
#Sta/Elev= 30
       0 3093.78    10.4 3091.86      19 3087.31    27.5 3084.34    34.6 3082.71
    40.2 3082.04    56.8 3078.07    61.5  3077.6   131.7 3077.99   148.4 3078.42
   152.6 3078.98   160.9 3078.42   169.2 3079.09   181.7 3078.62   190.8 3079.22
   206.7 3078.98     215 3077.84   219.2 3077.39   223.3 3077.83   231.7  3078.1
     240 3077.83   258.8 3078.53   269.1    3080   284.9 3080.59   301.7 3080.14
   309.8 3080.58   325.9 3083.82   358.1 3086.93   370.2 3090.02     386 3096.06
#Mann= 5 ,-1,0
       0      .1       0   82.18     .08       0  182.18      .1       0
     215    .045       0   223.3      .1       0
#XS Ineff= 2 , 0
            87.6 3084.92  280.19         3085.62
Permanent Ineff=
       F       F
Bank Sta=215,223.3
XS Rating Curve= 0 ,0
Exp/Cntr(USF)=0,0
Exp/Cntr=0.3,0.1

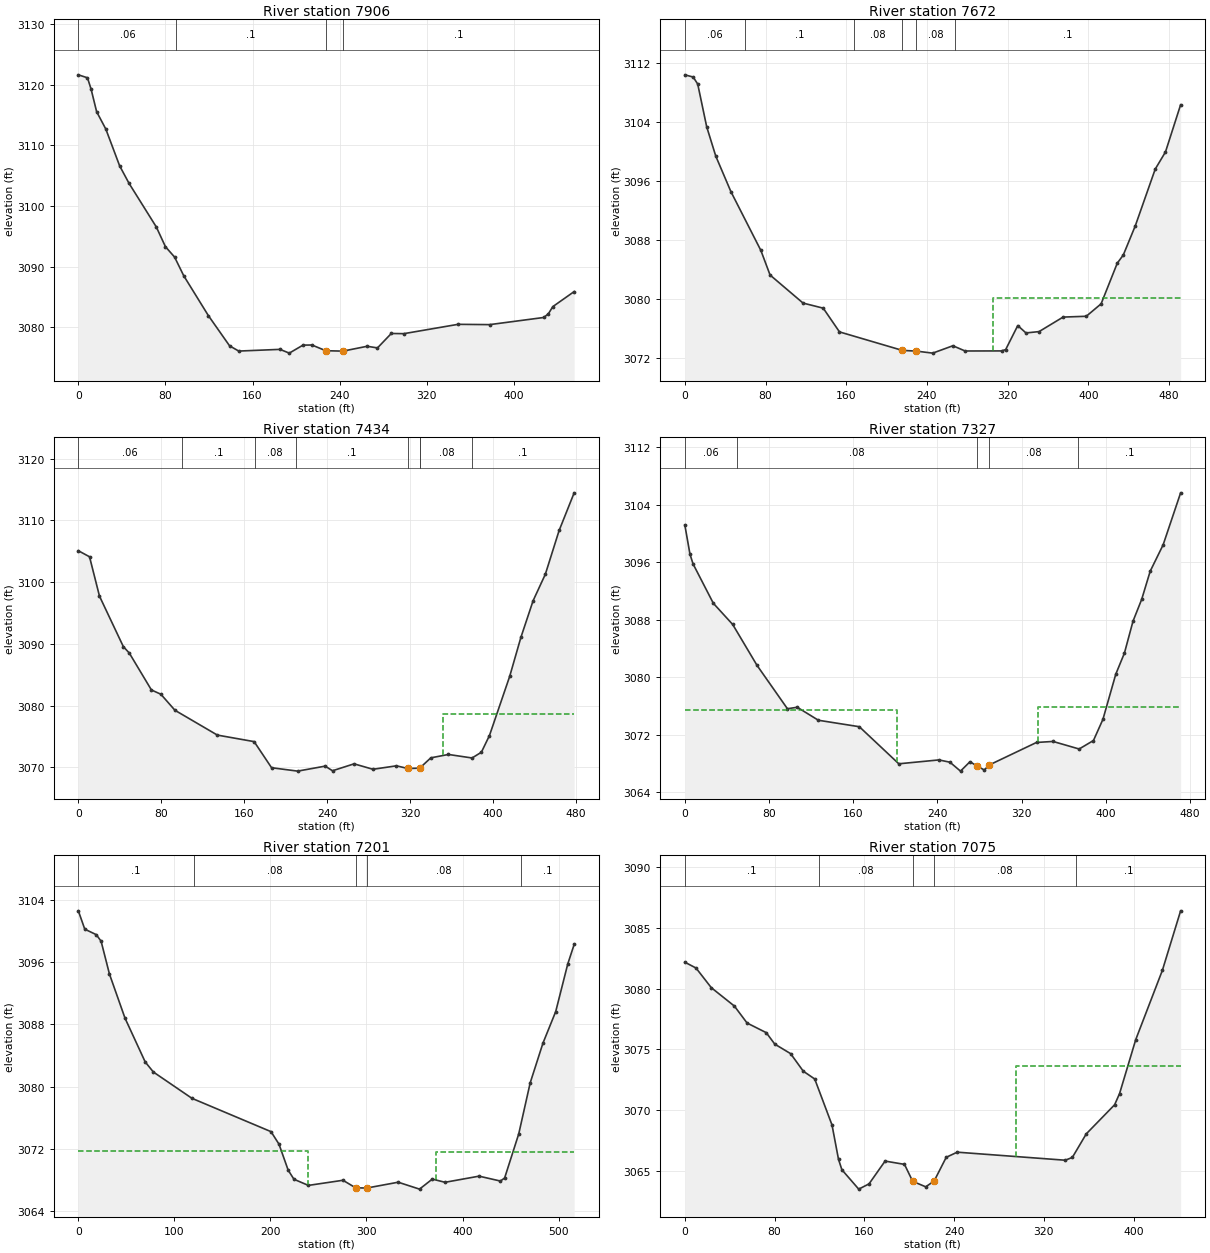
Type RM Length L Ch R = 1 ,7906    ,237.6,234.4,228.3
XS GIS Cut Line= 3
2319626.87879015612037.1755494452319531.81784248612326.869211689
2319571.03505981612472.091550068
#Sta/Elev= 30
       0 3121.65     8.4 3121.16    11.7  3119.3    16.8 3115.57    25.3 3112.68
    37.9 3106.65    46.5 3103.77    71.6 3096.56      80  3093.3    88.4 3091.59
    96.8 3088.51   119.4 3081.94   138.9 3076.95   147.3 3076.09   185.2 3076.37
   193.7 3075.75   206.3 3077.07   214.5 3077.09   227.2 3076.15     243 3076.08
   265.2 3076.88   274.7 3076.61   287.4 3078.99   298.9 3078.96   348.7  3080.5
   377.7 3080.45   427.4 3081.63   431.6 3082.23   435.7 3083.42   455.3  3085.9
#Mann= 4 ,-1,0
       0     .06       0      90      .1       0   227.2    .045       0
     243      .1       0
Bank Sta=227.2,243
XS Rating Curve= 0 ,0
Exp/Cntr(USF)=0,0
Exp/Cntr=0.3,0.1

Type RM Length L Ch R = 1 ,7672    ,227.3,238.1,241
XS GIS Cut Line= 4
2319414.25933811611973.7948910692319356.67117534612087.392890602
2319377.35130544612309.4774691122319314.52742507612435.671951243
#Sta/Elev= 30
       0 3110.46     8.3 3110.16    12.8 3109.21    21.7 3103.41    30.7 3099.43
    45.7 3094.61    75.4 3086.63    84.5  3083.3   117.2 3079.49   137.2  3078.8
   153.3 3075.58   215.53073.075   229.6 3072.97   245.7  3072.7   265.7  3073.7
   277.8 3072.99     314    3073     318 3073.18     330 3076.44   338.1 3075.44
   351.1 3075.62   374.9 3077.59   397.9  3077.7   412.6 3079.39   428.6  3084.9
   434.6 3086.02   446.5 3089.98   466.2 3097.66   476.4    3100   491.4  3106.4
#Mann= 6 ,-1,0
       0     .06       0      60      .1       0  167.36     .08       0
   215.5    .045       0   229.6     .08       0  267.36      .1       0
#XS Ineff= 2 , 0
                          305.15         3080.14
Permanent Ineff=
       F       F
Bank Sta=215.5,229.6
XS Rating Curve= 0 ,0
Exp/Cntr(USF)=0,0
Exp/Cntr=0.3,0.1

Type RM Length L Ch R = 1 ,7434    ,106,107.2,106.4
XS GIS Cut Line= 2
2319320.84557453611935.204391299 2319093.2916304612355.901683122
#Sta/Elev= 30
       0 3105.08    10.8  3104.1    20.4 3097.72    43.4 3089.55    49.2 3088.49
    70.5 3082.52    79.6 3081.83    93.2 3079.23   134.1 3075.21   169.6 3074.15
   186.4 3069.92   211.6 3069.37   238.1 3070.18   245.2 3069.43     266 3070.55
   284.2 3069.67   306.9 3070.23   317.7  3069.8   329.3 3069.85     340 3071.52
     357 3072.07   379.8  3071.5   388.8 3072.43   396.6 3075.14   416.1 3084.72
   426.9 3091.03   438.7 3096.98   450.5 3101.27   463.8 3108.36   478.3 3114.46
#Mann= 8 ,-1,0
       0     .06       0     100      .1       0     170     .08       0
     210      .1       0   317.7    .045       0   329.3      .1       0
     330     .08       0     380      .1       0
#XS Ineff= 2 , 0
                          352.16         3078.59
Permanent Ineff=
       F       F
Bank Sta=317.7,329.3
XS Rating Curve= 0 ,0
Exp/Cntr(USF)=0,0
Exp/Cntr=0.3,0.1

Type RM Length L Ch R = 1 ,7327    ,122.9,126.1,123.5
XS GIS Cut Line= 4
2319275.69668653611921.6257690942319155.46387924612046.808197665
2319052.21696883612245.291482328 2319037.0859561612317.386307699
#Sta/Elev= 30
       0 3101.19     4.9 3097.12     7.8 3095.76    27.1 3090.27    45.5 3087.32
    68.6 3081.63    97.5 3075.59   106.8  3075.8   126.9 3073.99   165.8 3073.09
   203.3 3067.93   241.4 3068.47   251.9 3068.15   261.9 3066.91   270.9 3068.22
   277.23067.653   284.5 3067.07     289 3067.75   334.1  3070.9   349.8 3071.04
   374.6 3069.99   388.2 3071.17   397.2 3074.12   409.4  3080.4   417.6 3083.33
   425.8 3087.79     434 3090.81   442.1 3094.73   454.4 3098.41     471 3105.64
#Mann= 5 ,-1,0
       0     .06       0      50     .08       0   277.2    .045       0
     289     .08       0  373.57      .1       0
#XS Ineff= 2 , 0
          201.29 3075.47  335.75         3075.82
Permanent Ineff=
       F       F
Bank Sta=277.2,289
XS Rating Curve= 0 ,0
Exp/Cntr(USF)=0,0
Exp/Cntr=0.3,0.1

Type RM Length L Ch R = 1 ,7201    ,125.7,125.7,126.2
XS GIS Cut Line= 3
2319223.16388144611850.8429290862319102.17178432611940.754487497
2318944.54905229 612270.43020167
#Sta/Elev= 30
       0 3102.63     6.7 3100.27    18.7 3099.56    23.7 3098.72    32.4 3094.49
    48.6 3088.81    69.6 3083.18    78.1 3081.88   118.3 3078.49   200.6  3074.2
   208.9 3072.59   218.5 3069.23   224.5 3068.07   239.5 3067.28   275.5 3067.94
   288.7 3066.97   300.3 3066.94     333 3067.69   355.2  3066.8   368.5 3068.09
   381.8 3067.68   417.2 3068.47   439.4 3067.84   443.8 3068.23   458.5 3073.91
   470.4 3080.47   483.7 3085.59     497 3089.66   509.5 3095.77   516.2  3098.3
#Mann= 5 ,-1,0
       0      .1       0     120     .08       0   288.7    .045       0
   300.3     .08       0  460.74      .1       0
#XS Ineff= 2 , 0
          238.65 3071.71  371.98         3071.64
Permanent Ineff=
       F       F
Bank Sta=288.7,300.3
XS Rating Curve= 0 ,0
Exp/Cntr(USF)=0,0
Exp/Cntr=0.3,0.1

Type RM Length L Ch R = 1 ,7075    ,244.1,241.3,239.4
XS GIS Cut Line= 4
2319067.22720818611838.8296610292318976.24334077611930.802483519
2318912.95021561  612043.5433627 2318852.6239557612216.610501794
#Sta/Elev= 30
       0 3082.16      10 3081.68    23.6 3080.07    44.2 3078.56    55.5 3077.17
    72.6 3076.38    80.2 3075.44    94.3 3074.66   105.6 3073.22   115.8 3072.58
   131.2 3068.81     137 3065.99     140 3065.14     155 3063.55   164.2 3063.98
   178.5 3065.85   195.8 3065.58   203.1 3064.19   214.7 3063.74   222.2 3064.21
     233 3066.16   242.8 3066.58   339.1 3065.92   345.4 3066.15   357.8 3068.08
   383.1 3070.47   387.5 3071.39   401.9 3075.81   425.6 3081.48   441.9 3086.37
#Mann= 5 ,-1,0
       0      .1       0     120     .08       0   203.1    .045       0
   222.2     .08       0  348.66      .1       0
#XS Ineff= 2 , 0
                          295.49         3073.64
Permanent Ineff=
       F       F
Bank Sta=203.1,222.2
XS Rating Curve= 0 ,0
Exp/Cntr(USF)=0,0
Exp/Cntr=0.3,0.1

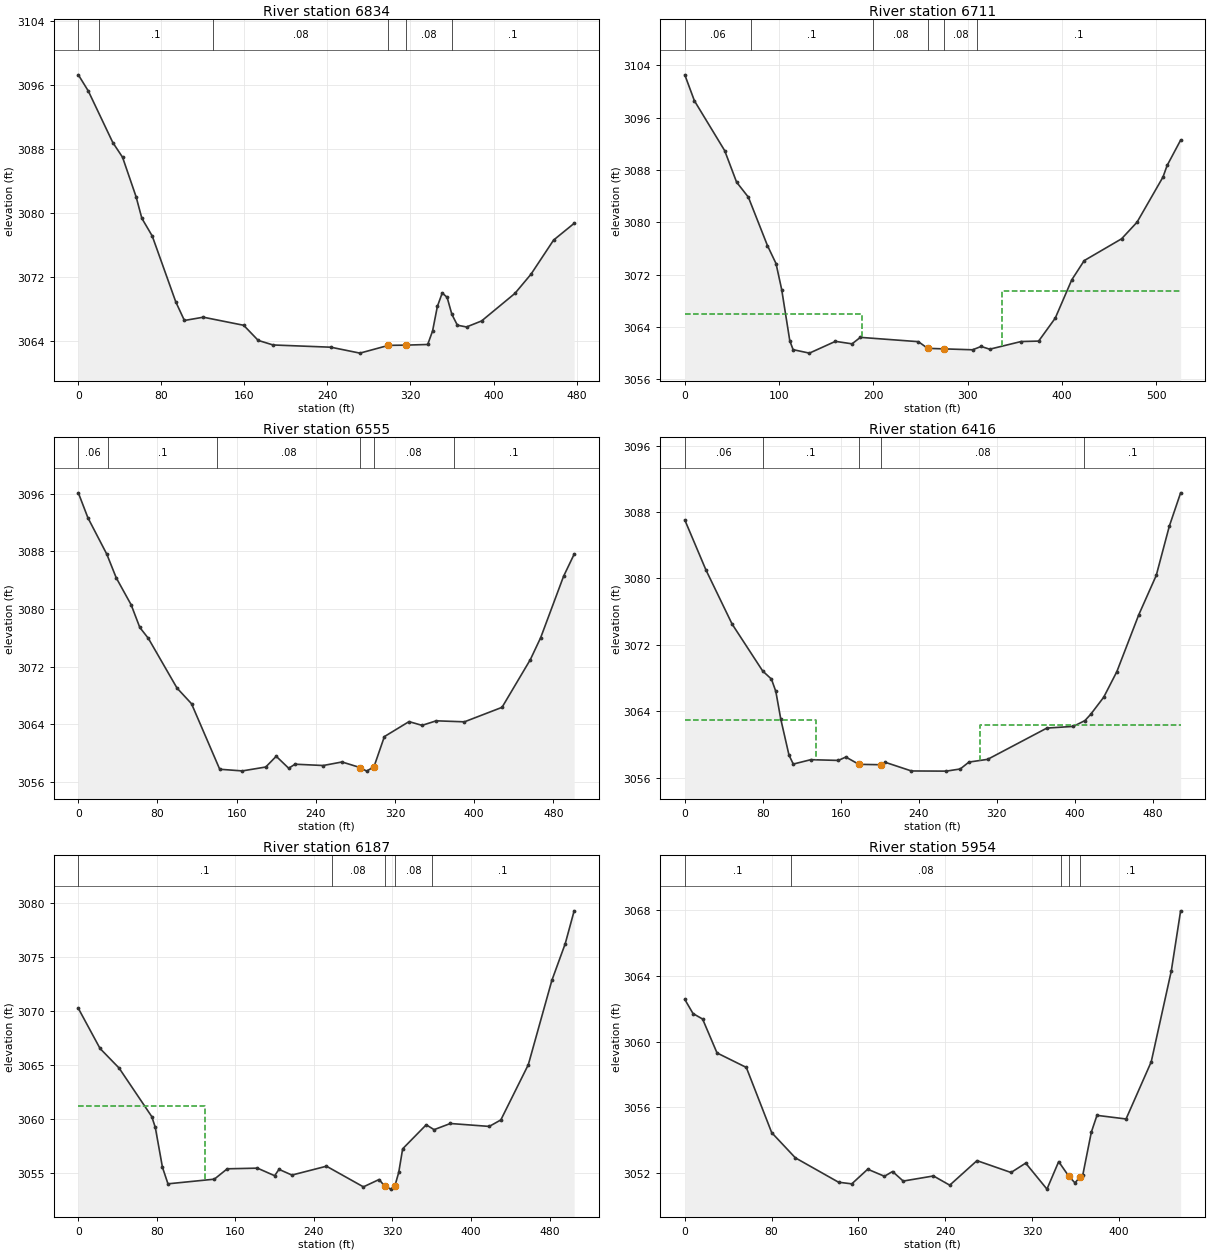
Type RM Length L Ch R = 1 ,6834    ,122.5,122.8,122.6
XS GIS Cut Line= 2
2318892.83568396 611716.685458972318646.75221834612126.106246723
#Sta/Elev= 30
       0 3097.26     9.6 3095.24    33.2  3088.8    42.6 3086.96    55.6 3082.04
    61.2 3079.33    71.2 3077.12    93.9 3068.88   102.2 3066.56   120.4 3066.97
   159.3 3065.96   173.3 3064.07   187.6  3063.5   243.3 3063.22   271.3 3062.48
   298.8 3063.45   315.7 3063.48   336.6 3063.56   341.3 3065.25   345.9 3068.31
   350.6    3070   355.3 3069.45   359.9 3067.32   365.2 3065.97     374 3065.75
   388.5  3066.5   420.6 3069.94   436.1 3072.34   457.9 3076.61   477.7  3078.7
#Mann= 6 ,-1,0
       0     .06       0      20      .1       0     130     .08       0
   298.8    .045       0   315.7     .08       0     360      .1       0
Bank Sta=298.8,315.7
XS Rating Curve= 0 ,0
Exp/Cntr(USF)=0,0
Exp/Cntr=0.3,0.1

Type RM Length L Ch R = 1 ,6711    ,154.8,155.7,157.7
XS GIS Cut Line= 2
2318774.93356705611643.8610445222318557.04090149612122.128593453
#Sta/Elev= 30
       0 3102.56    10.2 3098.59    42.3 3090.97    54.9 3086.16    67.4 3083.86
    87.6 3076.47    96.7 3073.72   102.7 3069.75   111.3 3061.92   114.8 3060.56
   132.1 3060.03   159.7 3061.83   177.3 3061.45   186.1 3062.44   247.6 3061.78
   257.5 3060.76   274.9 3060.68   305.1 3060.54   314.1 3061.05   323.2 3060.63
   356.4  3061.8   375.1 3061.87   392.7 3065.38   410.2 3071.23   423.4 3074.17
     463  3077.5   479.4 3080.04   506.9 3086.94   511.3 3088.71   525.6 3092.58
#Mann= 6 ,-1,0
       0     .06       0      70      .1       0     200     .08       0
   257.5    .045       0   274.9     .08       0     310      .1       0
#XS Ineff= 2 , 0
          188.13 3066.03   336.2         3069.53
Permanent Ineff=
       F       F
Bank Sta=257.5,274.9
XS Rating Curve= 0 ,0
Exp/Cntr(USF)=0,0
Exp/Cntr=0.3,0.1

Type RM Length L Ch R = 1 ,6555    ,151.3,138.8,141.3
XS GIS Cut Line= 2
2318673.76526545611608.9851697932318402.74147599612030.490191198
#Sta/Elev= 30
       0  3096.1     9.7 3092.63    28.8 3087.58    38.3 3084.31    53.4 3080.56
    62.1 3077.43    70.8  3075.9    99.7 3069.02   114.4 3066.84   142.9 3057.75
   165.7 3057.52   189.4 3058.06     200 3059.55   212.6 3057.89     219 3058.45
   247.5 3058.27   266.5 3058.76   284.9 3057.98   291.4 3057.49   298.8  3058.1
   309.3 3062.28   334.2 3064.36   347.4 3063.84   361.7 3064.47   390.2 3064.33
   428.2 3066.34   456.8 3072.96   467.3 3076.02   490.4 3084.52   501.1 3087.59
#Mann= 6 ,-1,0
       0     .06       0      30      .1       0     140     .08       0
   284.9    .045       0   298.8     .08       0     380      .1       0
Bank Sta=284.9,298.8
XS Rating Curve= 0 ,0
Exp/Cntr(USF)=0,0
Exp/Cntr=0.3,0.1

Type RM Length L Ch R = 1 ,6416    ,242.5,229.7,224.2
XS GIS Cut Line= 2
2318568.77514557611561.897097013 2318338.5489329612015.497551731
#Sta/Elev= 30
       0 3087.05    21.6 3081.05    48.5 3074.51    79.9 3068.85    88.9 3067.87
    93.4 3066.38    98.5 3063.03   106.9 3058.71   111.3 3057.63   129.3 3058.16
   157.6 3058.07   165.2 3058.48   178.6  3057.6   201.1 3057.55   205.5 3057.85
   232.5  3056.8   268.3 3056.78   282.6 3057.04   291.5 3057.87   310.7  3058.2
   371.5 3061.97   398.6 3062.17   410.5 3062.87   416.4 3063.62   429.8 3065.69
   443.3 3068.78   465.7 3075.61   483.7 3080.37   497.1  3086.3   508.7 3090.32
#Mann= 5 ,-1,0
       0     .06       0      80      .1       0   178.6    .045       0
   201.1     .08       0     410      .1       0
#XS Ineff= 2 , 0
           134.3  3062.9  302.42         3062.34
Permanent Ineff=
       F       F
Bank Sta=178.6,201.1
XS Rating Curve= 0 ,0
Exp/Cntr(USF)=0,0
Exp/Cntr=0.3,0.1

Type RM Length L Ch R = 1 ,6187    ,222.6,232.6,237.3
XS GIS Cut Line= 4
2318428.92195192611511.3742164472318369.66234014611562.249959839
2318289.75644478611737.2994097592318293.84695861611971.876650843
#Sta/Elev= 30
       0 3070.24    22.1 3066.53    41.5 3064.72    74.8 3060.23    78.4 3059.23
    85.7 3055.54    91.3 3054.01   138.5 3054.44   151.7  3055.4   182.5 3055.46
     200 3054.76   204.4 3055.35   217.6 3054.82   252.8 3055.64   290.4 3053.73
   306.4 3054.41   312.1 3053.79   318.4 3053.52   322.53053.831   326.4 3055.07
   330.4 3057.25   354.4 3059.47   362.4 3059.02     379 3059.59   418.6 3059.32
   430.4 3059.92   458.4 3065.03   482.4 3072.83     496 3076.22   505.1 3079.26
#Mann= 5 ,-1,0
       0      .1       0   258.1     .08       0   312.1    .045       0
   322.5     .08       0  360.53      .1       0
#XS Ineff= 2 , 0
          129.47 3061.17
Permanent Ineff=
       F       F
Bank Sta=312.1,322.5
XS Rating Curve= 0 ,0
Exp/Cntr(USF)=0,0
Exp/Cntr=0.3,0.1

Type RM Length L Ch R = 1 ,5954    ,446.4,434.2,428.6
XS GIS Cut Line= 4
 2318300.3457511611446.3443531542318266.89039931611516.291468408
2318207.09528291611595.2785278352318037.75724798611818.819978284
#Sta/Elev= 30
       0 3062.56     7.6  3061.7    16.4 3061.37    29.7 3059.31    56.7 3058.43
    80.1 3054.47   101.9 3052.94   141.7 3051.46   153.9 3051.36   168.6 3052.25
     184 3051.82   191.5 3052.11   201.3 3051.53   229.2 3051.84   244.2 3051.28
   269.3 3052.77   300.7 3052.05   314.2 3052.62   333.8 3051.04   344.6 3052.71
   353.83051.836   359.6 3051.42   364.3 3051.78   366.9 3051.92   374.7  3054.5
   379.9 3055.52   406.7  3055.3   429.9 3058.77   448.4 3064.29     457 3067.94
#Mann= 5 ,-1,0
       0      .1       0   97.54     .08       0   346.6      .1       0
   353.8    .045       0   364.3      .1       0
Bank Sta=353.8,364.3
XS Rating Curve= 0 ,0
Exp/Cntr(USF)=0,0
Exp/Cntr=0.3,0.1