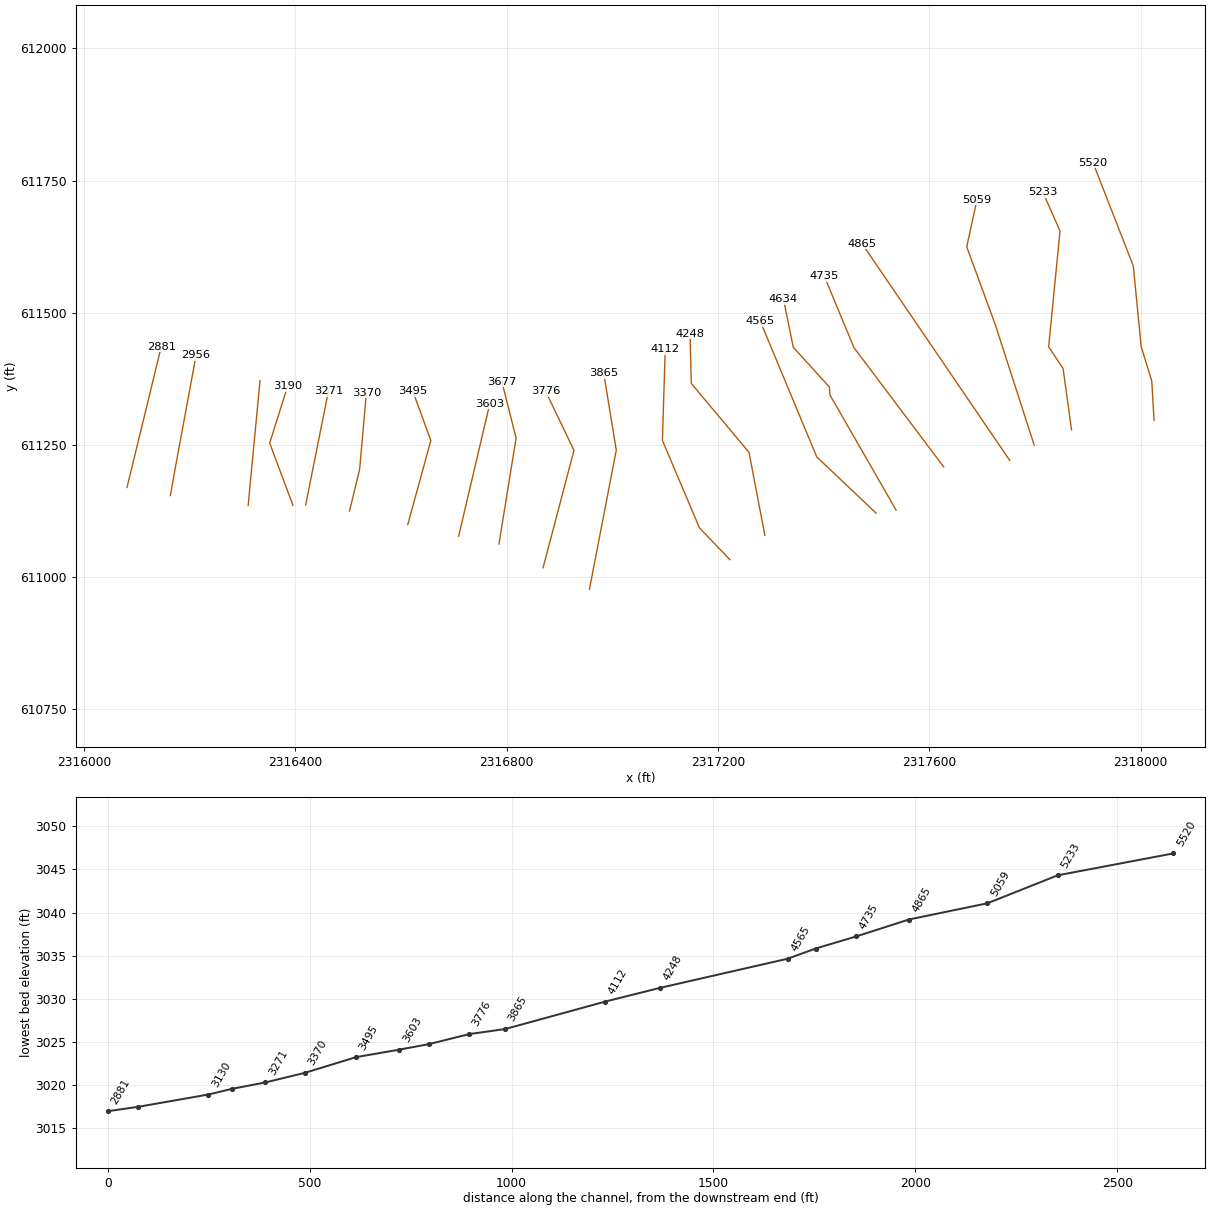
HEC-RAS study ELKLCKRN2.prj: ELKLCKRN2

--- ELKLCKRN2.g01 (geometry) --- (continued)

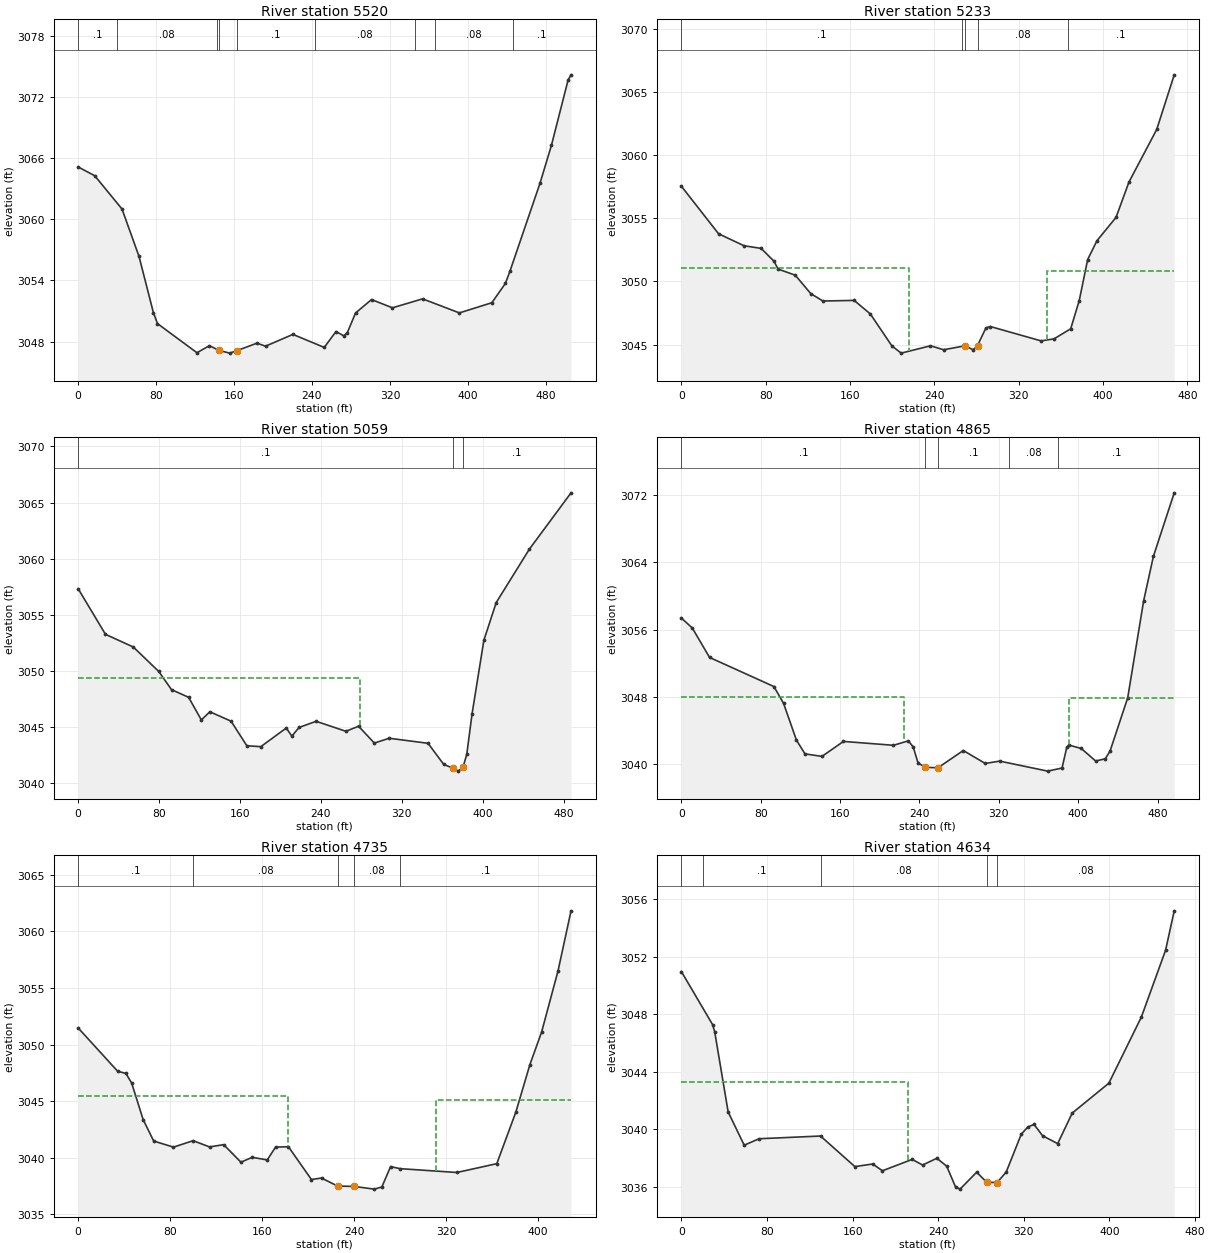
Type RM Length L Ch R = 1 ,5520    ,210.1,286.4,283.4
XS GIS Cut Line= 5
2318025.20737527611296.2430402942318020.86113251611370.397126094
2318000.82137292611435.9327961672317985.83974721611588.504329551
 2317909.6113101611783.955816325
#Sta/Elev= 30
       0 3065.14      17 3064.28      45 3061.01    62.4 3056.37    77.2 3050.84
    81.4 3049.76   121.9  3046.9   134.7 3047.59   144.5 3047.13   155.5 3046.86
   162.8  3047.1   183.6 3047.84   192.3 3047.54   220.4  3048.7   252.6 3047.42
   264.6 3048.98   272.7 3048.56   276.3 3048.88   284.7  3050.8   301.1 3052.12
   322.6 3051.31   353.5 3052.19   391.3 3050.81   424.6 3051.81   438.5  3053.7
   443.1 3054.88     474 3063.53   485.8 3067.27   502.9 3073.69   505.9 3074.19
#Mann= 9 ,-1,0
       0      .1       0      40     .08       0  142.81      .1       0
   144.5    .045       0   162.8      .1       0  242.81     .08       0
  346.12      .1       0  366.12     .08       0  446.12      .1       0
Bank Sta=144.5,162.8
XS Rating Curve= 0 ,0
Exp/Cntr(USF)=0,0
Exp/Cntr=0.3,0.1

Type RM Length L Ch R = 1 ,5233    ,233.3,174.4,179.1
XS GIS Cut Line= 5
2317868.99770404611278.2031505772317853.01342698611394.218346168
2317825.68012757611435.223722299 2317847.2091503611654.514699286
2317814.58843324611728.398150623
#Sta/Elev= 30
       0 3057.55    35.3 3053.78    59.5 3052.83    75.7 3052.62    87.8 3051.61
    91.8 3050.98     108  3050.5   122.7 3049.04   134.3 3048.45   163.9  3048.5
   179.2 3047.43   199.7 3044.89   208.5 3044.32   236.3  3044.9   248.7 3044.59
   269.3  3044.9   276.9 3044.58   280.9 3044.92   288.9 3046.32     293 3046.43
   341.2 3045.29   353.5 3045.45   369.3 3046.25   377.4 3048.49   385.4 3051.74
   394.2 3053.23   412.3 3055.08   424.6 3057.89   450.9 3062.05   467.5 3066.38
#Mann= 5 ,-1,0
       0      .1       0  266.39     .08       0   269.3    .045       0
   280.9     .08       0  366.39      .1       0
#XS Ineff= 2 , 0
          215.78 3051.07  347.02          3050.8
Permanent Ineff=
       F       F
Bank Sta=269.3,280.9
XS Rating Curve= 0 ,0
Exp/Cntr(USF)=0,0
Exp/Cntr=0.3,0.1

Type RM Length L Ch R = 1 ,5059    ,192.3,194.2,195.7
XS GIS Cut Line= 4
2317798.29433147 611249.298442722317725.19654093611475.740855801
2317670.67149868611624.6076070722317690.01850387611713.432125837
#Sta/Elev= 30
       0 3057.32      27 3053.26    54.5 3052.13    79.7 3049.95    92.3 3048.33
   109.2 3047.65   121.8 3045.63   130.2 3046.36   151.2 3045.52   166.8 3043.33
   180.6 3043.25   205.8 3044.91   211.3 3044.19   218.4 3044.96   235.3 3045.51
   264.8 3044.62   277.3 3045.07   292.9 3043.57   307.6    3044     346 3043.55
   361.5 3041.67   370.8 3041.33   375.8 3041.07   380.5  3041.4   384.3 3042.57
   389.5 3046.16   401.2 3052.73   413.4 3056.09   446.2 3060.85   487.4 3065.87
#Mann= 3 ,-1,0
       0      .1       0   370.8    .045       0   380.5      .1       0
#XS Ineff= 2 , 0
          278.58 3049.34
Permanent Ineff=
       F       F
Bank Sta=370.8,380.5
XS Rating Curve= 0 ,0
Exp/Cntr(USF)=0,0
Exp/Cntr=0.3,0.1

Type RM Length L Ch R = 1 ,4865    ,129.1,130.1,132
XS GIS Cut Line= 2
 2317752.1806912611220.0711921332317472.45584281611630.667308876
#Sta/Elev= 30
       0 3057.38      11  3056.2    28.4  3052.7    93.3 3049.24     103 3047.24
     116 3042.87   124.6 3041.24   141.7 3040.94   163.4 3042.72   213.8 3042.26
   228.8 3042.79   233.7 3042.07   238.5 3040.18   245.73039.644   258.73039.592
   284.2 3041.64   306.3  3040.1   320.8 3040.38   369.3 3039.19   383.7 3039.56
   388.5 3042.02   390.8 3042.28   403.1 3041.88   417.6 3040.39   427.3 3040.66
   432.1 3041.57   449.9  3047.9     466 3059.45   475.8 3064.71   496.8 3072.26
#Mann= 5 ,-1,0
       0      .1       0   245.7    .045       0   258.7      .1       0
     330     .08       0     380      .1       0
#XS Ineff= 2 , 0
          224.64 3047.94   390.5         3047.87
Permanent Ineff=
       F       F
Bank Sta=245.7,258.7
XS Rating Curve= 0 ,0
Exp/Cntr(USF)=0,0
Exp/Cntr=0.3,0.1

Type RM Length L Ch R = 1 ,4735    ,101,100.9,98.5
XS GIS Cut Line= 3
2317627.07468411611208.0082132322317457.28411167611433.573878014
2317401.05223919611568.859034259
#Sta/Elev= 30
       0 3051.47    34.3 3047.65    41.5 3047.45    46.5 3046.61    56.5 3043.38
    65.7 3041.48    82.9 3040.94     100 3041.51   114.3 3040.96   126.6 3041.16
   141.6 3039.61   151.4 3040.04   164.5 3039.81   171.7 3040.94   182.9 3040.98
   202.9 3038.08   211.7 3038.21   225.7  3037.5     240 3037.47   257.6 3037.23
   264.2 3037.42   271.8 3039.22     280 3039.04   329.5  3038.7   364.2 3039.48
   380.8 3044.04     393 3048.23   403.2 3051.11   417.5 3056.52   428.8 3061.82
#Mann= 5 ,-1,0
       0      .1       0     100     .08       0   225.7    .045       0
     240     .08       0     280      .1       0
#XS Ineff= 2 , 0
          182.73 3045.48  311.59         3045.12
Permanent Ineff=
       F       F
Bank Sta=225.7,240
XS Rating Curve= 0 ,0
Exp/Cntr(USF)=0,0
Exp/Cntr=0.3,0.1

Type RM Length L Ch R = 1 ,4634    ,72.2,69.2,66.6
XS GIS Cut Line= 5
2317536.94959552611126.2443946832317411.86896524611343.859164707
2317410.59263228611359.1751602512317342.30881881 611434.47880501
2317323.80199086611525.098445313
#Sta/Elev= 30
       0 3050.98    29.1 3047.29    31.1  3046.8    43.7  3041.2    58.7 3038.88
    72.6 3039.33     130 3039.52   162.1 3037.39   178.7 3037.57   187.9  3037.1
   215.6 3037.89   225.4  3037.5   238.7 3037.97   247.9 3037.42   256.3 3035.95
   260.4 3035.82   275.9    3037   285.3  3036.3     295 3036.28   303.5 3037.01
   317.6 3039.65   323.6 3040.14   329.5 3040.33   337.5 3039.54   351.6 3038.99
   365.2 3041.12   399.4  3043.2   429.8 3047.81   452.4 3052.46   460.5 3055.21
#Mann= 5 ,-1,0
       0     .06       0      20      .1       0     130     .08       0
   285.3    .045       0     295     .08       0
#XS Ineff= 2 , 0
          211.76 3043.26
Permanent Ineff=
       F       F
Bank Sta=285.3,295
XS Rating Curve= 0 ,0
Exp/Cntr(USF)=0,0
Exp/Cntr=0.3,0.1

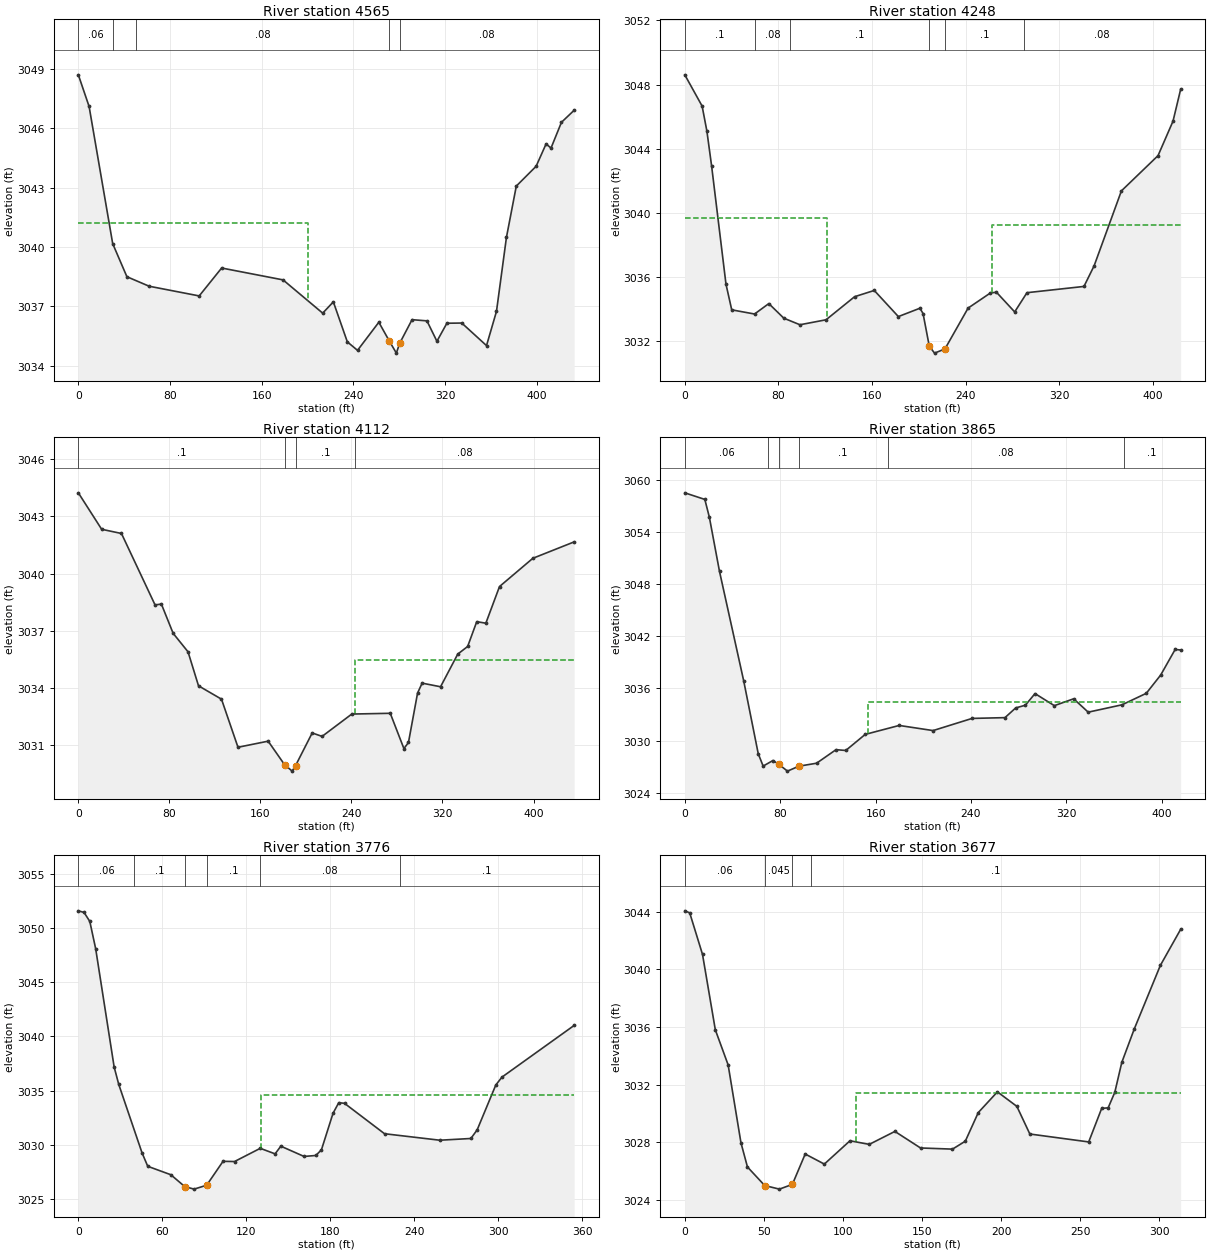
Type RM Length L Ch R = 1 ,4565    ,309.9,316.6,317.9
XS GIS Cut Line= 3
2317498.96743337611120.5730655582317386.76928046611226.923252923
2317279.89413679611483.830357982
#Sta/Elev= 30
       0  3048.7     9.4  3047.1      30 3040.17    42.4  3038.5    61.8 3038.02
   105.5 3037.53   125.1 3038.94   178.7 3038.34   213.3 3036.66   222.6 3037.23
   234.8 3035.21   243.7 3034.78   262.3  3036.2   271.43035.257   277.6 3034.64
   280.53035.137   291.3 3036.33   304.3 3036.27     313 3035.24   321.7 3036.15
   334.7 3036.16   356.3 3035.02     365 3036.75   373.7 3040.49   382.3 3043.08
   399.6 3044.08   408.3 3045.21   412.6    3045   421.7  3046.3   432.8 3046.91
#Mann= 5 ,-1,0
       0     .06       0      30      .1       0      50     .08       0
   271.4    .045       0   280.5     .08       0
#XS Ineff= 2 , 0
          200.48 3041.19
Permanent Ineff=
       F       F
Bank Sta=271.4,280.5
XS Rating Curve= 0 ,0
Exp/Cntr(USF)=0,0
Exp/Cntr=0.3,0.1

Type RM Length L Ch R = 1 ,4248    ,139.1,136.3,133.8
XS GIS Cut Line= 4
2317288.51935338611078.6077831442317258.57880443 611235.59336413
2317149.33626096611365.8752122682317146.90864888611459.742879249
#Sta/Elev= 30
       0 3048.61    14.8 3046.66    18.9 3045.09    22.9 3042.93    35.2 3035.55
    40.1 3033.95    59.6 3033.69    71.8 3034.34    84.6 3033.43    98.4 3033.02
   120.7 3033.33   145.1 3034.77   161.9 3035.16   182.5 3033.53   200.9 3034.05
   203.6 3033.72   208.9 3031.69   213.4 3031.25   222.3 3031.51   242.1 3034.06
   261.1    3035   266.3 3035.05   281.9 3033.82   292.4 3035.02   341.1 3035.41
   349.8  3036.7   373.1 3041.37   404.4 3043.57   417.2 3045.72   423.7  3047.7
#Mann= 6 ,-1,0
       0      .1       0      60     .08       0      90      .1       0
   208.9    .045       0   222.3      .1       0  289.82     .08       0
#XS Ineff= 2 , 0
          121.49  3039.7  262.48         3039.23
Permanent Ineff=
       F       F
Bank Sta=208.9,222.3
XS Rating Curve= 0 ,0
Exp/Cntr(USF)=0,0
Exp/Cntr=0.3,0.1

Type RM Length L Ch R = 1 ,4112    ,259.5,246.6,240.7
XS GIS Cut Line= 4
2317222.31992803611032.4259393352317164.77653064611092.666683471
2317094.64551508611258.1039509482317100.04020859611430.734143098
#Sta/Elev= 30
       0 3044.23    20.5 3042.32    37.9  3042.1    67.4 3038.36      73  3038.4
    83.3 3036.87    96.4  3035.9   105.6 3034.12   125.8 3033.42   140.3  3030.9
   166.8 3031.22   181.2 3029.99   187.9 3029.65   190.9 3029.94   205.5 3031.65
   214.2 3031.47   240.3 3032.64   274.1 3032.68   286.1 3030.83   290.1 3031.15
   298.1 3033.74   302.1 3034.26   318.3 3034.07   333.4 3035.78   342.1 3036.18
   350.1 3037.48   358.1  3037.4   370.1 3039.32   399.4  3040.8   435.7 3041.66
#Mann= 4 ,-1,0
       0      .1       0   181.2    .045       0   190.9      .1       0
  243.31     .08       0
#XS Ineff= 2 , 0
                          243.16         3035.49
Permanent Ineff=
       F       F
Bank Sta=181.2,190.9
XS Rating Curve= 0 ,0
Exp/Cntr(USF)=0,0
Exp/Cntr=0.3,0.1

Type RM Length L Ch R = 1 ,3865    ,91.6,89.3,89.5
XS GIS Cut Line= 3
2316956.62827587610976.6528006362317007.36536828611239.752002859
2316983.50284068611385.651488693
#Sta/Elev= 30
       0 3058.53    16.8 3057.77    20.6 3055.72    29.1 3049.48    49.4 3036.87
    61.6 3028.48    65.7 3027.06    73.9  3027.7    78.6 3027.29    86.1 3026.48
    95.7 3027.05   110.5 3027.39   126.8 3028.95     135 3028.86   151.3 3030.71
   179.8 3031.74   208.2 3031.15   240.9 3032.55   268.5 3032.64   277.5 3033.76
   285.6 3034.07   293.7 3035.41   309.9 3034.02   326.1 3034.81   338.3 3033.27
   366.7 3034.12     387 3035.44   399.1 3037.55   411.2 3040.49   415.8 3040.43
#Mann= 6 ,-1,0
       0     .06       0      70      .1       0    78.6    .045       0
    95.7      .1       0     170     .08       0  367.95      .1       0
#XS Ineff= 2 , 0
                          153.78         3034.42
Permanent Ineff=
       F       F
Bank Sta=78.6,95.7
XS Rating Curve= 0 ,0
Exp/Cntr(USF)=0,0
Exp/Cntr=0.3,0.1

Type RM Length L Ch R = 1 ,3776    ,97.5,99.1,100.1
XS GIS Cut Line= 3
2316868.83914573611017.2174532142316927.28165869611239.299002491
2316873.33472365611351.688450506
#Sta/Elev= 30
       0 3051.61     4.1 3051.46     8.2 3050.63    12.4  3048.1    25.6 3037.17
    28.9 3035.56    45.5 3029.25    49.6    3028    66.1 3027.22      76 3026.13
    82.7 3025.89    91.7 3026.25   103.4 3028.46   111.6 3028.44     130 3029.66
   140.6 3029.15   144.7 3029.86   161.3 3028.91   169.7    3029   173.7 3029.52
     182  3032.9   186.1 3033.88   190.2 3033.82   218.8 3031.01   258.3 3030.41
   280.5 3030.57     285 3031.37   298.3 3035.51   302.7 3036.24   354.3 3041.02
#Mann= 6 ,-1,0
       0     .06       0      40      .1       0      76    .045       0
    91.7      .1       0     130     .08       0  229.64      .1       0
#XS Ineff= 2 , 0
                          130.76         3034.55
Permanent Ineff=
       F       F
Bank Sta=76,91.7
XS Rating Curve= 0 ,0
Exp/Cntr(USF)=0,0
Exp/Cntr=0.3,0.1

Type RM Length L Ch R = 1 ,3677    ,74.7,73.7,72.8
XS GIS Cut Line= 3
2316785.34975415611062.0967536112316817.71791517611262.599528869
2316790.74444765611369.594283378
#Sta/Elev= 30
       0 3044.07     3.1 3043.93    11.2 3041.04    19.3  3035.8    27.4 3033.36
    35.5 3027.95    39.6 3026.27    50.5 3024.98    59.8 3024.73      68 3025.06
    76.1 3027.17    88.2 3026.47   104.4 3028.09   116.6 3027.84   132.8 3028.74
     149 3027.59   169.2 3027.51   177.3 3028.06   185.5 3030.05   197.6 3031.49
   209.9 3030.48   218.1 3028.56   255.3 3028.01   263.5 3030.34   267.6 3030.38
   271.8 3031.46   276.2 3033.53   284.1 3035.86   300.6 3040.28   313.4 3042.78
#Mann= 4 ,-1,0
       0     .06       0    50.5    .045       0      68     .06       0
      80      .1       0
#XS Ineff= 2 , 0
                          108.14         3031.39
Permanent Ineff=
       F       F
Bank Sta=50.5,68
XS Rating Curve= 0 ,0
Exp/Cntr(USF)=0,0
Exp/Cntr=0.3,0.1

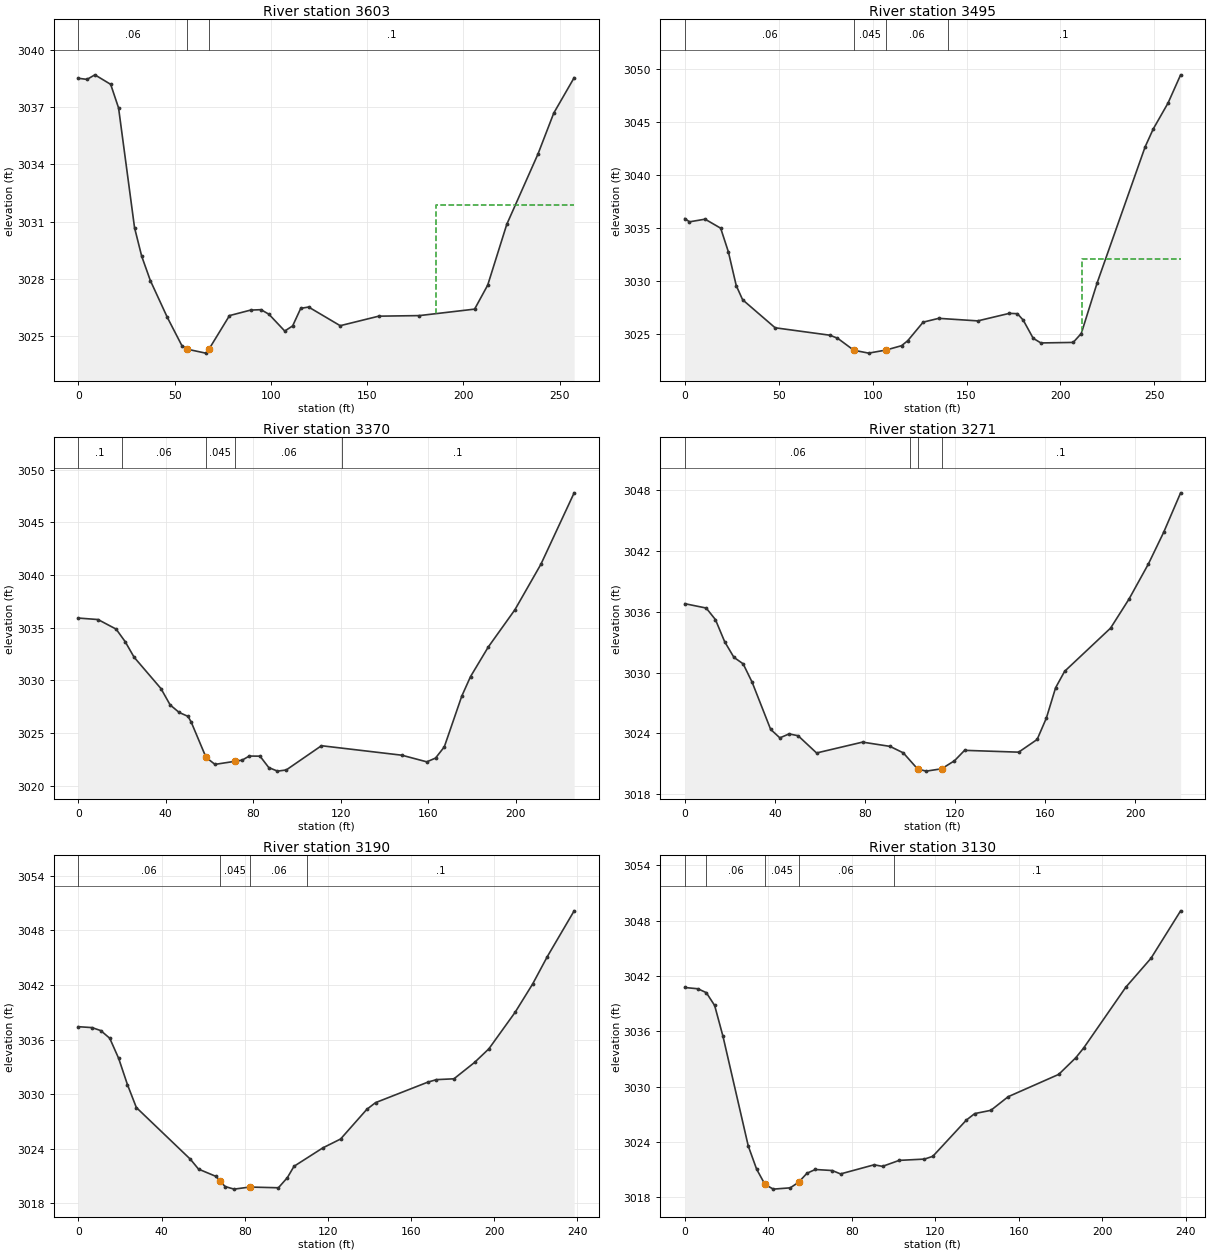
Type RM Length L Ch R = 1 ,3603    ,104.2,107.7,106.3
XS GIS Cut Line= 2
2316709.00655712611076.7891609422316767.90890706611327.452367193
#Sta/Elev= 30
       0 3038.52     4.5 3038.46     8.6  3038.7    16.8  3038.2    20.9 3036.96
    29.2 3030.67    32.9 3029.18    37.4  3027.9    46.2 3025.97    53.8 3024.48
    56.63024.296    66.1 3024.09    67.8 3024.29    78.5 3026.06    89.5 3026.35
    94.9 3026.37      99 3026.13   107.2 3025.25   111.3 3025.52   115.5 3026.44
   119.6 3026.51     136 3025.53     156 3026.03   177.1 3026.06   205.8  3026.4
   212.6 3027.66   222.5 3030.85   238.7 3034.54   246.9 3036.69   257.5 3038.55
#Mann= 3 ,-1,0
       0     .06       0    56.6    .045       0    67.8      .1       0
#XS Ineff= 2 , 0
                          185.51         3031.86
Permanent Ineff=
       F       F
Bank Sta=56.6,67.8
XS Rating Curve= 0 ,0
Exp/Cntr(USF)=0,0
Exp/Cntr=0.3,0.1

Type RM Length L Ch R = 1 ,3495    ,123.2,125.8,124.8
XS GIS Cut Line= 3
2316612.71185329611098.7676116132316656.36244059611257.862515328
2316622.47580045 611350.90718826
#Sta/Elev= 30
       0  3035.9     2.5 3035.59    10.8 3035.84    19.1 3034.99    23.2 3032.76
    27.4 3029.57    30.8 3028.24    48.1  3025.6    77.2  3024.9    81.3 3024.62
      90 3023.48    97.9 3023.21   107.1  3023.5   115.4 3023.91   118.7 3024.38
   126.9 3026.13   135.2 3026.49     156 3026.25   172.8 3026.96   177.1 3026.93
   180.2 3026.32   185.5 3024.61   189.6 3024.17   206.8 3024.22   211.1 3025.06
   219.6 3029.86   245.1 3042.66   249.4 3044.34   257.3 3046.79     264 3049.45
#Mann= 4 ,-1,0
       0     .06       0      90    .045       0   107.1     .06       0
     140      .1       0
#XS Ineff= 2 , 0
                           211.3         3032.12
Permanent Ineff=
       F       F
Bank Sta=90,107.1
XS Rating Curve= 0 ,0
Exp/Cntr(USF)=0,0
Exp/Cntr=0.3,0.1

Type RM Length L Ch R = 1 ,3370    ,99.2,98.2,98.5
XS GIS Cut Line= 3
2316502.46894257611124.4032274652316521.50910307611202.762325878
2316534.40650967611348.350261915
#Sta/Elev= 30
       0 3035.92       9 3035.78    17.3 3034.87    21.4 3033.69    25.5 3032.21
    37.8 3029.23      42 3027.68    46.1 3026.97    50.2 3026.59    51.7 3026.02
    58.4 3022.71    62.5 3022.04    71.6 3022.33    74.9 3022.44    78.2 3022.83
    83.1 3022.82    87.1 3021.74    91.1  3021.4    95.1 3021.51   111.2 3023.81
     148 3022.91   159.4 3022.28   163.4 3022.64   167.4  3023.7   175.4 3028.52
   179.4 3030.37   187.5 3033.17   199.7 3036.71   211.6 3041.03   226.8  3047.8
#Mann= 5 ,-1,0
       0      .1       0      20     .06       0    58.4    .045       0
    71.6     .06       0  120.64      .1       0
Bank Sta=58.4,71.6
XS Rating Curve= 0 ,0
Exp/Cntr(USF)=0,0
Exp/Cntr=0.3,0.1

Type RM Length L Ch R = 1 ,3271    ,78.8,81.6,89.2
XS GIS Cut Line= 2
2316419.40971141611135.8242315082316462.56725945611351.611971696
#Sta/Elev= 30
       0 3036.79     9.5 3036.36    13.6 3035.22    17.7 3033.04    21.8  3031.5
    25.9 3030.86    29.9 3029.04    38.1  3024.4    42.2 3023.56    46.3 3023.95
    50.3 3023.77    58.5 3022.07    78.9 3023.14    91.1 3022.72      97 3022.08
   103.4 3020.48   107.2 3020.28     114 3020.51   119.7  3021.3   124.2 3022.33
   148.2 3022.15   156.4  3023.4   160.5 3025.51   164.6  3028.5   168.6 3030.12
     189 3034.38   197.2 3037.25   205.8 3040.71   212.6 3043.84   220.1 3047.72
#Mann= 4 ,-1,0
       0     .06       0     100      .1       0   103.4    .045       0
     114      .1       0
Bank Sta=103.4,114
XS Rating Curve= 0 ,0
Exp/Cntr(USF)=0,0
Exp/Cntr=0.3,0.1

Type RM Length L Ch R = 1 ,3190    ,66.7,59.5,55
XS GIS Cut Line= 3
2316395.42019335611135.0317501712316351.38670616611253.092549158
2316385.20952965611360.304517967
#Sta/Elev= 30
       0 3037.41     6.6 3037.31    10.8 3036.98    15.1 3036.14    19.4 3033.92
    23.6 3031.05    27.9 3028.52    53.9 3022.83    57.8 3021.75    66.3 3020.94
    68.13020.439    70.6 3019.83    74.9 3019.55    82.43019.778    96.2  3019.7
   100.5 3020.81   103.7 3022.06   117.6 3024.09   126.1 3025.06   138.7 3028.32
   142.9 3029.06     168 3031.31   172.2 3031.59   180.6 3031.68   190.5 3033.48
   197.4 3034.98     210 3038.99   218.4 3042.09   225.5 3045.12   238.4 3050.15
#Mann= 4 ,-1,0
       0     .06       0    68.1    .045       0    82.4     .06       0
     110      .1       0
Bank Sta=68.1,82.4
XS Rating Curve= 0 ,0
Exp/Cntr(USF)=0,0
Exp/Cntr=0.3,0.1

Type RM Length L Ch R = 1 ,3130    ,177,174.1,174
XS GIS Cut Line= 2
2316310.61672573611134.9251159242316333.09461534611371.392514546
#Sta/Elev= 30
       0 3040.76     6.3 3040.62    10.3  3040.2    14.3 3038.81    18.3 3035.45
    30.4 3023.56    34.4 3021.05    38.4 3019.39    42.4 3018.88    50.5 3019.02
    54.5 3019.62    58.5  3020.6    62.5 3021.01    70.6  3020.9    74.6 3020.53
    90.7 3021.52    94.7 3021.35   102.7    3022   114.8 3022.14   118.8 3022.44
   134.9 3026.38   138.9 3027.08   146.6 3027.43   154.9 3028.91   179.1 3031.33
   187.3 3033.14   191.1 3034.21   211.2 3040.78   223.3 3043.93   237.5 3049.08
#Mann= 5 ,-1,0
       0      .1       0      10     .06       0    38.4    .045       0
    54.5     .06       0     100      .1       0
Bank Sta=38.4,54.5
XS Rating Curve= 0 ,0
Exp/Cntr(USF)=0,0
Exp/Cntr=0.3,0.1

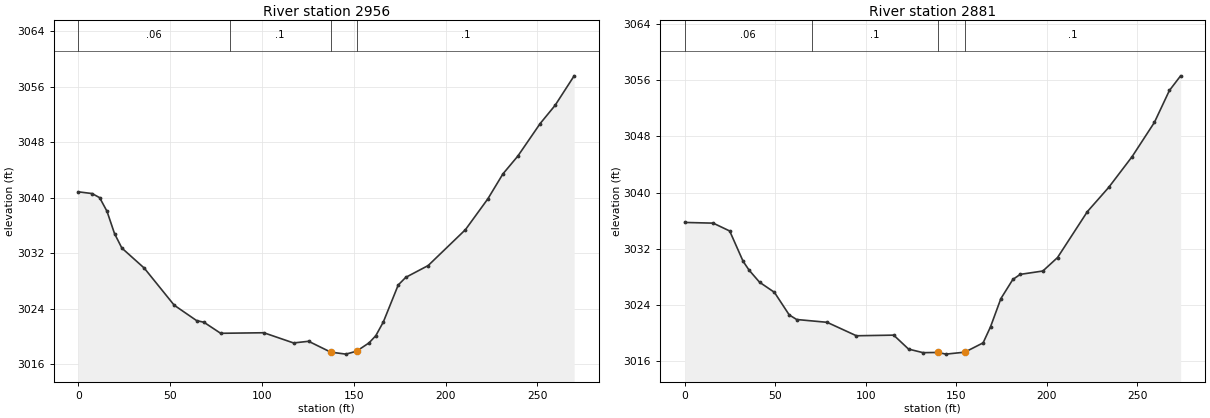
Type RM Length L Ch R = 1 ,2956    ,76.6,75.3,74.5
XS GIS Cut Line= 3
2316163.43119817611153.8065431912316174.33335768611215.237772752
2316212.10916917611419.342856344
#Sta/Elev= 30
       0 3040.83     7.5 3040.58    11.6 3039.99    15.6 3038.03    19.7 3034.82
    23.7 3032.73    35.9 3029.84    52.2  3024.5    64.4 3022.28    68.4 3022.04
    77.5 3020.45     101 3020.53   117.2 3019.06   125.4  3019.3   137.4 3017.74
   145.7 3017.45   151.5 3017.87   158.3 3019.07     162 3020.11   166.1 3022.09
   174.2 3027.41   178.3 3028.51   190.5 3030.21   210.8 3035.38     223 3039.82
   231.2 3043.41   239.3 3045.97   251.5 3050.67   259.6 3053.28     270 3057.54
#Mann= 4 ,-1,0
       0     .06       0   82.39      .1       0   137.4    .045       0
   151.5      .1       0
Bank Sta=137.4,151.5
XS Rating Curve= 0 ,0
Exp/Cntr(USF)=0,0
Exp/Cntr=0.3,0.1

Type RM Length L Ch R = 1 ,2881    ,201.2,206,208.8
XS GIS Cut Line= 2
2316081.34225178611169.0915081212316146.07857384611435.229721019
#Sta/Elev= 30
       0 3035.73    15.7 3035.63    24.8 3034.51    32.2 3030.19    35.5 3028.93
    41.3  3027.2    49.5 3025.76    57.7 3022.53    61.8 3021.88    78.6 3021.48
    94.8 3019.56   115.4 3019.65   123.6 3017.66   131.6 3017.15   140.1 3017.18
   144.2 3016.94   154.7 3017.22   164.8 3018.55   168.9 3020.85   174.6 3024.86
   181.2 3027.59   185.3 3028.32   197.8  3028.8   205.9 3030.72   222.4 3037.28
   234.2 3040.74   247.1 3045.12   259.4    3050   267.7 3054.56   273.9 3056.65
#Mann= 4 ,-1,0
       0     .06       0      70      .1       0   140.1    .045       0
   154.7      .1       0
Bank Sta=140.1,154.7
XS Rating Curve= 0 ,0
Exp/Cntr(USF)=0,0
Exp/Cntr=0.3,0.1