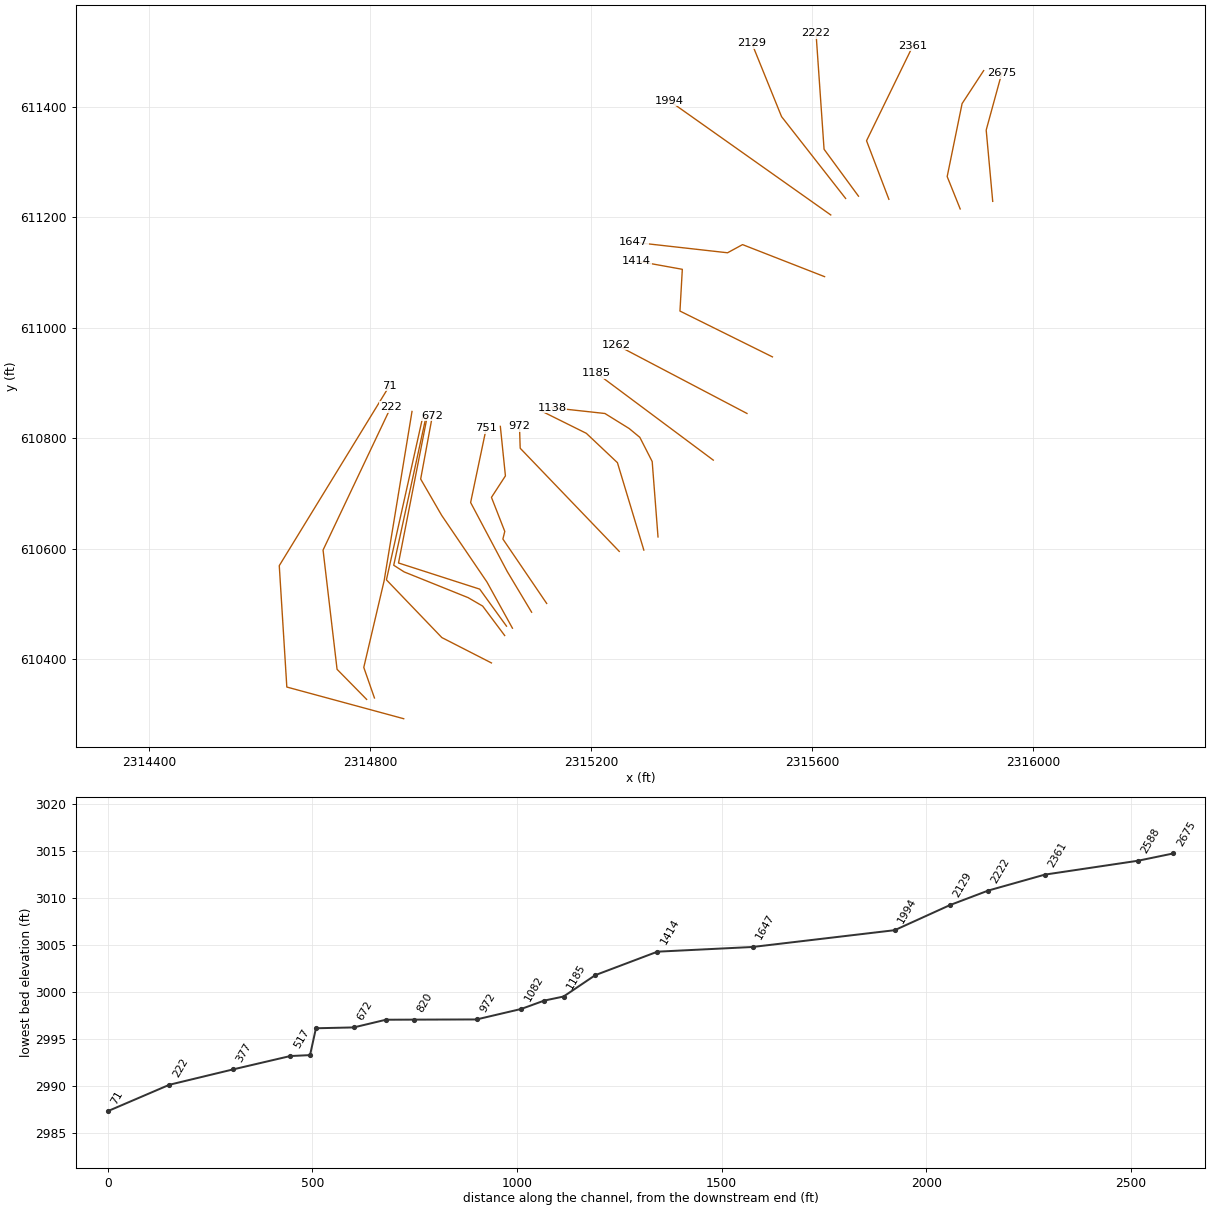
HEC-RAS study ELKLCKRN2.prj: ELKLCKRN2

--- ELKLCKRN2.g01 (geometry) --- (continued)

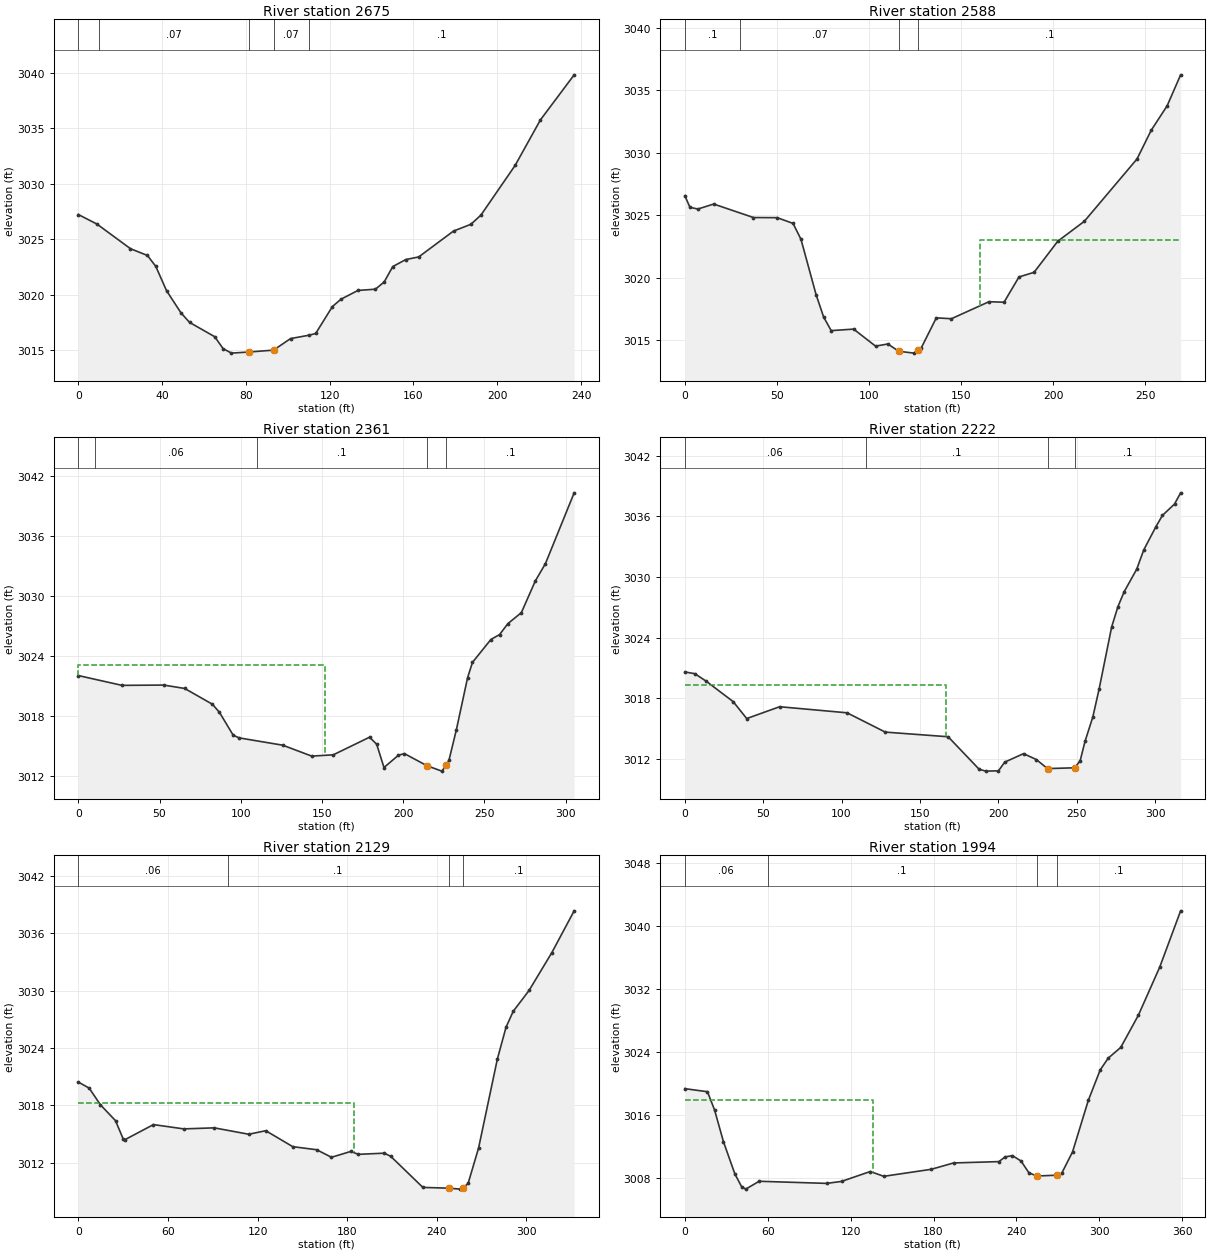
Type RM Length L Ch R = 1 ,2675    ,84.6,86.4,82.5
XS GIS Cut Line= 3
2315926.88473298611228.3388062282315915.07837118611357.347020498
2315943.35223002611460.735539125
#Sta/Elev= 30
       0 3027.24     8.9 3026.38    24.9 3024.16      33 3023.55      37 3022.56
    42.1 3020.38      49 3018.38    53.1 3017.52    65.1 3016.23    69.1 3015.16
    73.1 3014.75    81.4 3014.85    93.2 3015.02   101.3 3016.06     110 3016.36
   113.3 3016.52   121.3 3018.95   125.4 3019.61   133.5  3020.4   141.8 3020.51
     146 3021.16   150.1 3022.55   156.3 3023.18   162.5 3023.42   179.1 3025.75
   187.4 3026.36   192.2 3027.19   208.5 3031.66   220.6 3035.77   236.7 3039.83
#Mann= 5 ,-1,0
       0      .1       0      10     .07       0    81.4    .045       0
    93.2     .07       0     110      .1       0
Bank Sta=81.4,93.2
XS Rating Curve= 0 ,0
Exp/Cntr(USF)=0,0
Exp/Cntr=0.3,0.1

Type RM Length L Ch R = 1 ,2588    ,229.8,227.8,224.8
XS GIS Cut Line= 4
 2315868.0129579611214.6080211812315844.46461475611273.191704137
2315871.45905689611405.2921657062315910.51484553611465.024548329
#Sta/Elev= 30
       0 3026.56     2.8 3025.63     7.1 3025.49    15.7 3025.89    37.3 3024.81
    50.2  3024.8    58.8 3024.34    63.1 3023.07    71.3 3018.65    75.4 3016.86
    79.5 3015.77    91.7 3015.89   103.6 3014.53   110.3  3014.7   116.2 3014.12
   124.4 3013.97   126.83014.181   128.4 3014.38   136.6 3016.79   144.8 3016.72
   165.2 3018.08   173.4 3018.04   181.5 3020.06   189.7 3020.43   202.6 3022.92
     217 3024.51   245.6 3029.49   253.3 3031.78     262 3033.75   269.3 3036.22
#Mann= 4 ,-1,0
       0      .1       0      30     .07       0   116.2    .045       0
   126.8      .1       0
#XS Ineff= 2 , 0
                          160.39         3023.01
Permanent Ineff=
       F       F
Bank Sta=116.2,126.8
XS Rating Curve= 0 ,0
Exp/Cntr(USF)=0,0
Exp/Cntr=0.3,0.1

Type RM Length L Ch R = 1 ,2361    ,131,138.4,143.7
XS GIS Cut Line= 3
2315738.95903735611232.0295990092315698.49883607611338.035326376
2315782.65605474 611510.39578385
#Sta/Elev= 30
       0 3022.04    26.9 3021.06    52.6 3021.09    65.5 3020.75    82.6 3019.17
    86.9 3018.36    95.4 3016.07    99.1 3015.81   125.9 3015.08   143.7 3013.99
     157 3014.12   179.3 3015.88   183.7 3015.18   188.2 3012.85   197.1 3014.08
   200.8 3014.24   214.73013.027   223.8 3012.49   226.63013.067   228.2 3013.57
   232.7 3016.57   239.7 3021.84   242.7 3023.36     254 3025.64   259.4 3026.14
   264.5 3027.23   272.8 3028.33   281.4  3031.5   287.6 3033.22   305.3  3040.3
#Mann= 5 ,-1,0
       0      .1       0      10     .06       0     110      .1       0
   214.7    .045       0   226.6      .1       0
#XS Ineff= 2 , 0
          152.17 3023.09
Permanent Ineff=
       F       F
Bank Sta=214.7,226.6
XS Rating Curve= 0 ,0
Exp/Cntr(USF)=0,0
Exp/Cntr=0.3,0.1

Type RM Length L Ch R = 1 ,2222    ,90.2,93.6,97.2
XS GIS Cut Line= 3
2315683.93316361611237.6940271892315621.62445363611322.660449887
2315607.05878116 611533.05349657
#Sta/Elev= 30
       0  3020.6     6.4 3020.43    13.8 3019.67    30.9 3017.66    39.5 3015.99
    60.5 3017.16   103.5 3016.56   127.9 3014.65     168 3014.19   187.8 3010.97
   192.1 3010.79   200.1 3010.82   204.1 3011.68   216.1 3012.52   224.2 3011.94
   231.4 3011.04   248.7 3011.12   252.2 3011.81   255.3 3013.73   260.3 3016.15
   264.3 3018.91   272.3 3025.05   276.3 3027.06   280.3 3028.54   288.3 3030.77
   292.8 3032.68   300.3  3034.9   304.7 3036.09   312.4 3037.21   316.3 3038.32
#Mann= 4 ,-1,0
       0     .06       0  115.36      .1       0   231.4    .045       0
   248.7      .1       0
#XS Ineff= 2 , 0
          166.83 3019.34
Permanent Ineff=
       F       F
Bank Sta=231.4,248.7
XS Rating Curve= 0 ,0
Exp/Cntr(USF)=0,0
Exp/Cntr=0.3,0.1

Type RM Length L Ch R = 1 ,2129    ,128.7,134.8,141.1
XS GIS Cut Line= 3
2315660.67266822611233.5615656672315544.65400197611381.743822557
2315490.66511768611514.992983792
#Sta/Elev= 30
       0 3020.44     7.3  3019.8    14.8 3018.06    24.9  3016.4      30  3014.5
    31.4 3014.43    50.3 3015.99    70.6 3015.54      91 3015.65   114.1 3014.98
   125.5 3015.35   143.6 3013.68   159.6 3013.36   169.5 3012.57   182.4 3013.18
   187.5 3012.88   204.9    3013   209.2 3012.67   230.7 3009.42     248 3009.34
   255.7 3009.24   257.7 3009.37     261 3009.84     268 3013.54   280.6 3022.86
   286.4 3026.18   291.2 3027.84   301.8 3030.02   317.1 3033.99     332 3038.35
#Mann= 4 ,-1,0
       0     .06       0     100      .1       0     248    .045       0
   257.7      .1       0
#XS Ineff= 2 , 0
           184.3 3018.28
Permanent Ineff=
       F       F
Bank Sta=248,257.7
XS Rating Curve= 0 ,0
Exp/Cntr(USF)=0,0
Exp/Cntr=0.3,0.1

Type RM Length L Ch R = 1 ,1994    ,339.9,347.4,347
XS GIS Cut Line= 2
2315633.76251401611203.7074581092315340.83065671611410.863688689
#Sta/Elev= 30
       0 3019.35    16.4 3018.96    21.5 3016.66      28 3012.59    36.2 3008.52
    41.1 3006.88    44.1 3006.57    53.8 3007.57   102.6  3007.3   113.4 3007.55
   134.2 3008.81     144  3008.2   178.3 3009.09   194.5  3009.9   227.3 3010.07
   231.8 3010.67   237.1 3010.83   243.3 3010.15     249 3008.65   254.7 3008.24
   269.1 3008.34   272.7 3008.57   280.6 3011.31     292 3017.86   300.6 3021.73
   306.4 3023.23   315.5  3024.6   328.2 3028.68   343.7 3034.82   358.8 3041.97
#Mann= 4 ,-1,0
       0     .06       0      60      .1       0   254.7    .045       0
   269.1      .1       0
#XS Ineff= 2 , 0
          136.55 3017.87
Permanent Ineff=
       F       F
Bank Sta=254.7,269.1
XS Rating Curve= 0 ,0
Exp/Cntr(USF)=0,0
Exp/Cntr=0.3,0.1

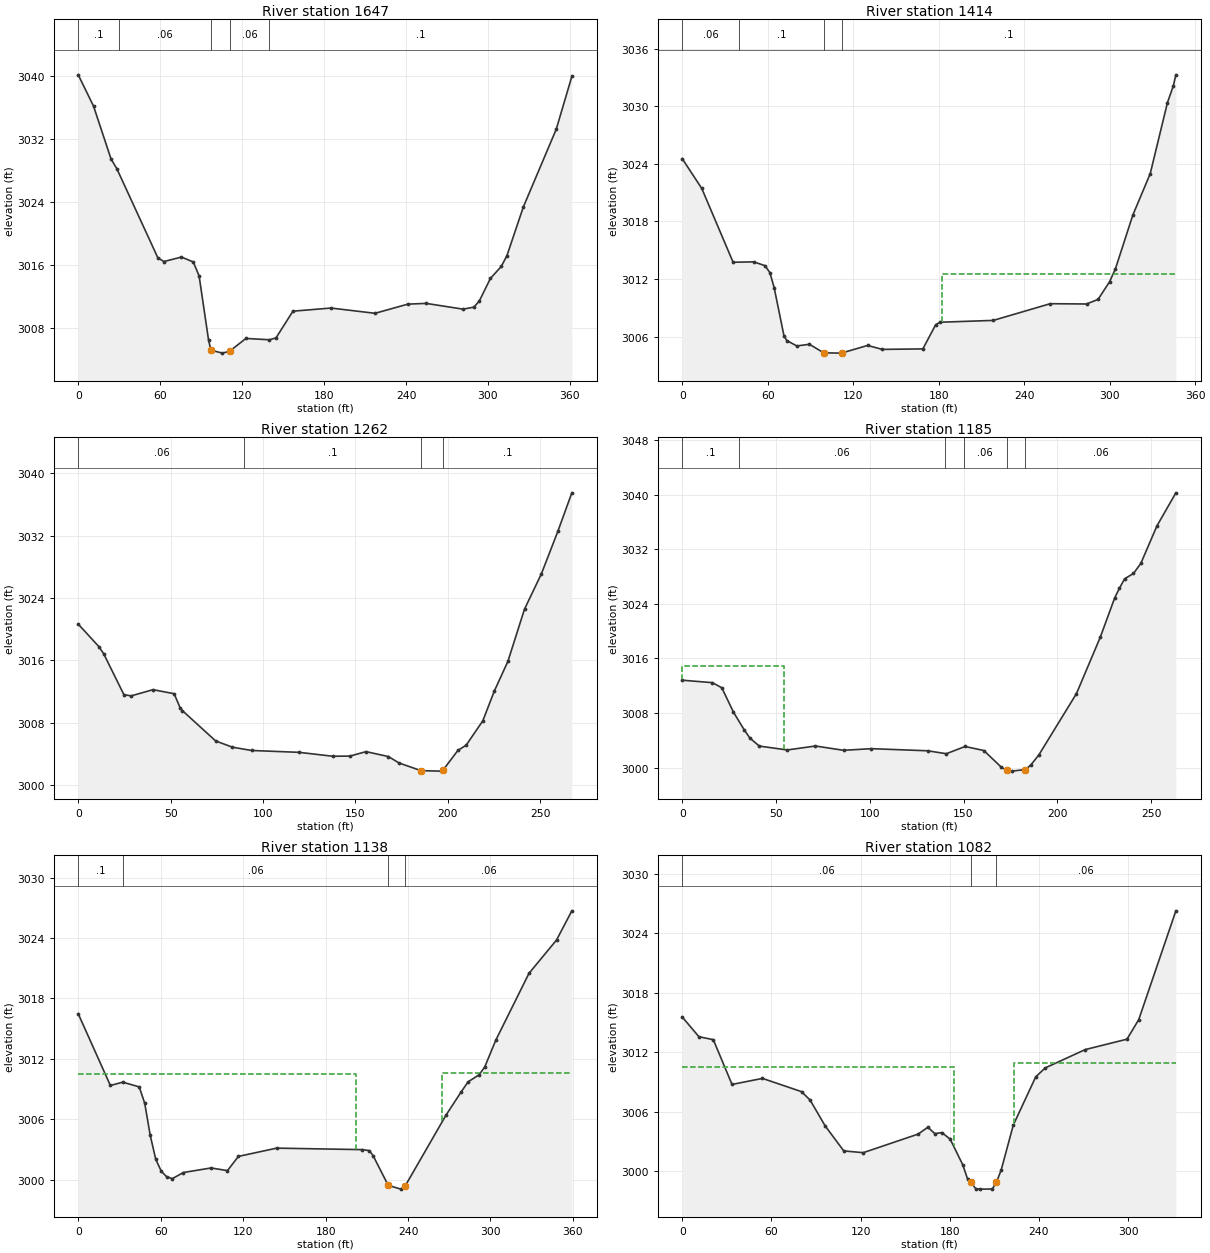
Type RM Length L Ch R = 1 ,1647    ,232.1,232.3,227.4
XS GIS Cut Line= 4
 2315622.5718898611092.0345445572315474.07233133611150.046958445
2315446.93787933611135.2690965852315276.90353868611154.346012541
#Sta/Elev= 30
       0 3040.21    11.2 3036.23      24 3029.51    28.3 3028.25    58.3 3016.92
    62.7 3016.44    75.6 3017.01    84.2 3016.39    88.5 3014.62    95.4 3006.48
    97.1 3005.16   105.6 3004.78   110.8 3005.02   122.8 3006.65     140 3006.48
   144.8 3006.72   157.2 3010.12   185.1 3010.52   217.3 3009.85   241.4 3011.02
   254.8 3011.11   281.7 3010.38   289.7 3010.63   293.7 3011.43   301.8 3014.29
   309.8 3015.83   313.9  3017.2   325.9 3023.39     350 3033.29   361.4    3040
#Mann= 5 ,-1,0
       0      .1       0      30     .06       0    97.1    .045       0
   110.8     .06       0     140      .1       0
Bank Sta=97.1,110.8
XS Rating Curve= 0 ,0
Exp/Cntr(USF)=0,0
Exp/Cntr=0.3,0.1

Type RM Length L Ch R = 1 ,1414    ,150.7,151.8,149.5
XS GIS Cut Line= 4
2315528.19104705610946.8234098262315360.79219345611029.792837989
2315365.07569451611105.3439637092315282.36931857611120.277059365
#Sta/Elev= 30
       0 3024.54    13.7 3021.44    35.7 3013.75    50.3 3013.79    58.1 3013.39
    61.5 3012.67    64.5 3011.11    71.4 3006.09    73.4 3005.59    80.4 3005.03
    89.3  3005.2    99.3 3004.31   111.6 3004.28   112.33004.307   130.1 3005.08
   140.4 3004.67   168.9 3004.72   177.9 3007.24   180.9  3007.5   218.3 3007.69
   258.3 3009.43   283.8  3009.4   291.9 3009.88     300 3011.73   304.1 3013.08
   316.3 3018.67   328.5 3022.98   340.6 3030.39   344.7 3032.12   346.5 3033.28
#Mann= 4 ,-1,0
       0     .06       0      40      .1       0    99.3    .045       0
   112.3      .1       0
#XS Ineff= 2 , 0
                          182.61         3012.48
Permanent Ineff=
       F       F
Bank Sta=99.3,112.3
XS Rating Curve= 0 ,0
Exp/Cntr(USF)=0,0
Exp/Cntr=0.3,0.1

Type RM Length L Ch R = 1 ,1262    ,78.9,77.6,76
XS GIS Cut Line= 2
 2315482.0781783610844.4289748752315245.55387016610968.663965011
#Sta/Elev= 30
       0 3020.64    11.2 3017.75    13.8 3016.83    24.7  3011.6    28.6 3011.43
    40.5 3012.23    51.9 3011.71    55.3 3009.84    56.4 3009.54    74.4 3005.65
    83.5 3004.85    93.8 3004.43   119.6 3004.19   137.7 3003.69   147.1 3003.71
   155.8 3004.28   167.9 3003.65   173.8 3002.81   185.6 3001.84   196.4 3001.78
   197.5 3001.92   205.5 3004.43     210 3005.11     219 3008.23   225.3 3012.08
   232.6 3015.87   241.6 3022.57   250.7 3027.08   259.7 3032.58   267.2 3037.48
#Mann= 4 ,-1,0
       0     .06       0      90      .1       0   185.6    .045       0
   197.5      .1       0
Bank Sta=185.6,197.5
XS Rating Curve= 0 ,0
Exp/Cntr(USF)=0,0
Exp/Cntr=0.3,0.1

Type RM Length L Ch R = 1 ,1185    ,46.2,47.1,47.9
XS GIS Cut Line= 2
2315421.10579999610759.958015663  2315210.049206 610917.26727826
#Sta/Elev= 30
       0 3012.82    16.1 3012.46    21.1 3011.71    27.3 3008.14      33 3005.57
    36.1 3004.33    41.1 3003.17      56  3002.6      71 3003.18      86 3002.55
   100.9 3002.79   130.9 3002.48   140.8 3002.05   150.8 3003.11   160.8 3002.52
   170.2 3000.06     173 2999.64   175.8  2999.5   182.8 2999.73   185.7 3000.34
   190.2  3001.9   210.2 3010.86   222.9 3019.12   230.6 3024.89   233.1 3026.29
   235.9 3027.68   240.6 3028.46   244.5 3029.92   253.1 3035.42   263.2 3040.27
#Mann= 6 ,-1,0
       0      .1       0      30     .06       0     140      .1       0
     150     .06       0     173    .045       0   182.8     .06       0
#XS Ineff= 2 , 0
           54.11 3014.96
Permanent Ineff=
       F       F
Bank Sta=173,182.8
XS Rating Curve= 0 ,0
Exp/Cntr(USF)=0,0
Exp/Cntr=0.5,0.3

Type RM Length L Ch R = 1 ,1138    ,58.9,56,53.6
XS GIS Cut Line= 6
2315321.07842121610620.9040813042315310.53621042610757.412567366
2315288.20548891610801.1435636432315268.90628063610817.124086092
2315224.98748101610844.3658955762315129.07756024610854.881086286
#Sta/Elev= 30
       0 3016.48    23.4 3009.36    32.4 3009.69    44.4 3009.22    48.4 3007.59
    52.4 3004.41    56.4 3002.04    60.5 3000.83    64.4  3000.3    68.5 3000.11
    76.5 3000.72    96.6 3001.17   108.6 3000.91   116.6 3002.32   144.4 3003.14
   206.8 3002.99   211.9 3002.89   214.6 3002.39   225.6 2999.44   234.9 2999.07
     238  2999.4   267.6 3006.41   278.7 3008.73   283.7 3009.72   291.7 3010.42
   295.8 3011.19   303.8 3013.84     328 3020.49   348.1 3023.81   359.2  3026.7
#Mann= 4 ,-1,0
       0      .1       0    32.4     .06       0   225.6    .045       0
     238     .06       0
#XS Ineff= 2 ,-1
       0     202  3010.5     265  357.73  3010.6
Permanent Ineff=
       F       F
Bank Sta=225.6,238
XS Rating Curve= 0 ,0
Exp/Cntr(USF)=0,0
Exp/Cntr=0.5,0.3

Type RM Length L Ch R = 1 ,1082    ,110.2,109.4,108.6
XS GIS Cut Line= 4
2315295.40259007610597.1494834282315247.61990155610755.363274285
2315191.34251286610808.4551504112315111.17377991610848.274057506
#Sta/Elev= 30
       0 3015.56    11.2 3013.57    20.9 3013.27    33.5 3008.75      54 3009.36
    80.3 3008.02    86.1 3007.16    96.1 3004.58   108.7 3002.04   121.8 3001.86
   158.8 3003.74   165.3 3004.43     170 3003.78   174.7 3003.89   180.3 3003.23
   188.8 3000.63     192 2999.21   194.5 2998.85   197.5 2998.21   200.1 2998.18
   208.6 2998.19   211.4 2998.85   214.6 3000.09   222.8 3004.65   237.9 3009.52
   244.3 3010.42   271.2 3012.27   299.3 3013.32   307.2 3015.29   332.2 3026.28
#Mann= 3 ,-1,0
       0     .06       0   194.5    .045       0   211.4     .06       0
#XS Ineff= 2 , 0
             183  3010.5     223          3010.9
Permanent Ineff=
       F       F
Bank Sta=194.5,211.4
XS Rating Curve= 0 ,0
Exp/Cntr(USF)=0,0
Exp/Cntr=0.5,0.3

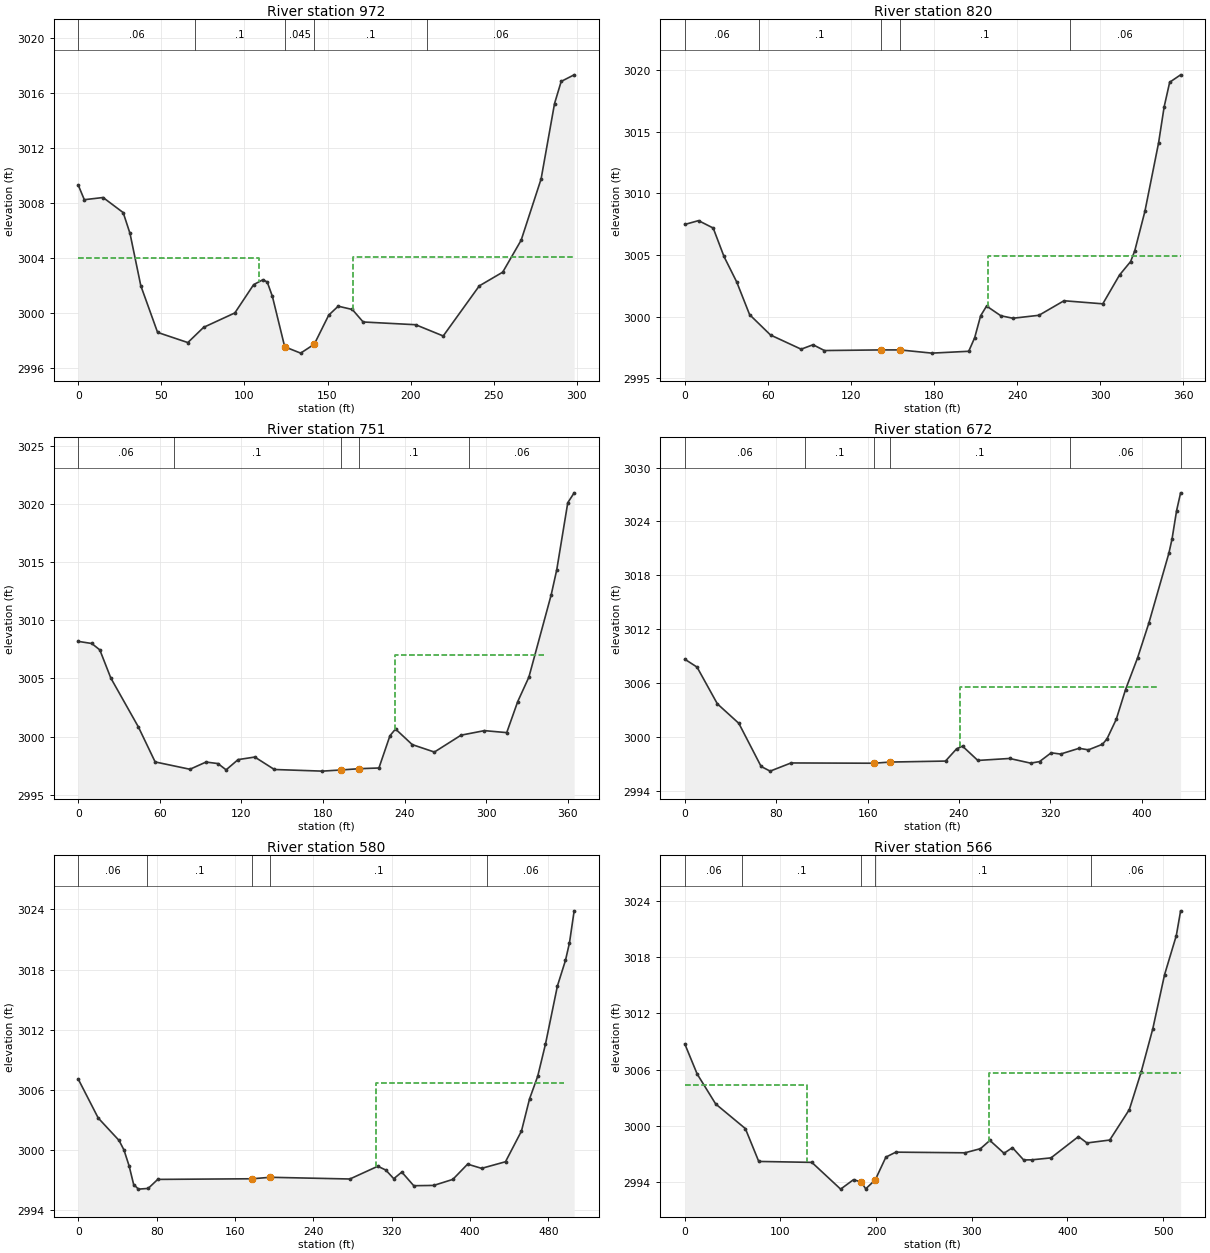
Type RM Length L Ch R = 1 ,972     ,159,152.8,147.1
XS GIS Cut Line= 3
2315250.90104505610594.7804714792315071.63101612610781.462126315
2315070.34088353610821.026192404
#Sta/Elev= 30
       0 3009.29     3.6 3008.24    14.9  3008.4      27  3007.3    31.1 3005.78
    37.6 3001.97    47.7 2998.57    65.9 2997.83    75.4 2998.94    94.2 2999.99
   105.5 3002.05   111.1 3002.41   113.7 3002.24   116.8 3001.19   124.22997.521
   133.8 2997.06     142 2997.71   150.7 2999.83   156.4 3000.48   164.9 3000.24
   171.4 2999.33     203 2999.13   219.6 2998.31   241.3 3001.96   255.4 3002.96
   266.5 3005.29   278.5 3009.75   286.6 3015.25   290.6 3016.86   298.4 3017.34
#Mann= 5 ,-1,0
       0     .06       0      70      .1       0   124.2    .045       0
     142      .1       0     210     .06       0
#XS Ineff= 2 , 0
          108.64 3003.96  165.22         3004.03
Permanent Ineff=
       F       F
Bank Sta=124.2,142
XS Rating Curve= 0 ,0
Exp/Cntr(USF)=0,0
Exp/Cntr=0.3,0.1

Type RM Length L Ch R = 1 ,820     ,60.1,68.5,65.9
XS GIS Cut Line= 6
2315119.54255515610500.556302257 2315040.2822782610617.149318338
 2315043.7283772610630.9337143282315019.62389111610692.568458467
2315044.87707687610731.4449350872315035.68747954610821.043509021
#Sta/Elev= 30
       0 3007.48     9.9 3007.79    20.5 3007.19    28.3 3004.88    37.5 3002.81
    46.8 3000.16    61.9 2998.51      84 2997.36    92.6 2997.72   100.8 2997.25
   141.4  2997.3   155.4  2997.3   178.4 2997.04     205 2997.19   209.3 2998.29
   213.6 3000.07   217.9 3000.86   228.2 3000.07   236.9 2999.87   255.7 3000.11
   273.8 3001.29   301.8 3001.04   313.9 3003.38   321.9 3004.47   324.9 3005.35
   332.2 3008.54   342.1 3014.11   346.1 3017.02   350.1 3019.02     358 3019.62
#Mann= 5 ,-1,0
       0     .06       0   53.44      .1       0   141.4    .045       0
   155.4      .1       0  277.93     .06       0
#XS Ineff= 2 , 0
                             219         3004.96
Permanent Ineff=
       F       F
Bank Sta=141.4,155.4
XS Rating Curve= 0 ,0
Exp/Cntr(USF)=0,0
Exp/Cntr=0.3,0.1

Type RM Length L Ch R = 1 ,751     ,72,78.7,77.8
XS GIS Cut Line= 4
 2315092.2813987610484.6888685142315048.11064352610558.440943757
2314981.87934038610683.2660710282315010.17073577 610817.76350736
#Sta/Elev= 30
       0 3008.18     9.9    3008    15.8 3007.45    23.9 3005.03    44.2 3000.82
    56.5 2997.82    82.1 2997.19    93.9 2997.81   102.7 2997.68   108.7 2997.14
   117.5 2998.02   129.8 2998.24   144.2 2997.17   179.5 2997.03   193.2 2997.13
   206.8 2997.24   221.1  2997.3   229.2 3000.07   233.3 3000.65   245.6 2999.31
   261.9 2998.67   281.5 3000.12   298.7 3000.51   315.1 3000.34   323.2 3003.01
   331.4 3005.11   347.8 3012.18   351.9 3014.34     360  3020.1   364.7 3020.95
#Mann= 5 ,-1,0
       0     .06       0      70      .1       0   193.2    .045       0
   206.8      .1       0  287.28     .06       0
#XS Ineff= 1 ,-1
  232.97  342.543007.042
Permanent Ineff=
       F
Bank Sta=193.2,206.8
XS Rating Curve= 0 ,0
Exp/Cntr(USF)=0,0
Exp/Cntr=0.3,0.1

Type RM Length L Ch R = 1 ,672     ,77.9,92.4,96.7
XS GIS Cut Line= 5
2315057.57130579610455.7848796892315011.44984852610539.356873332
2314929.39921094 610660.12275648 2314891.4797319610725.729536439
2314912.74765801610840.555579825
#Sta/Elev= 30
       0 3008.67    10.7 3007.79    28.5  3003.7    47.3 3001.53    66.8 2996.73
    74.7 2996.21      93 2997.12   165.4 2997.09   179.9 2997.22   228.2 2997.33
   237.9 2998.69   243.1 2998.99   256.5  2997.4   284.3 2997.62   302.7  2997.1
   310.5 2997.27   320.7 2998.25   328.9 2998.11   345.1 2998.75   353.3 2998.58
   365.6  2999.2   369.6 2999.81   377.7 3001.99   385.8 3005.29   396.3 3008.81
   406.2 3012.69   423.8  3020.5   426.5 3022.06   430.5 3025.22     434 3027.19
#Mann= 6 ,-1,0
       0     .06       0  105.45      .1       0   165.4    .045       0
   179.9      .1       0  337.23     .06       0  434.01      .1       0
#XS Ineff= 1 ,-1
  240.97  413.463005.554
Permanent Ineff=
       F
Bank Sta=165.4,179.9
XS Rating Curve= 0 ,0
Exp/Cntr(USF)=0,0
Exp/Cntr=0.3,0.1

Type RM Length L Ch R = 1 ,580     ,17,14.4,14.1
XS GIS Cut Line= 4
2315046.84790624610459.4388091092314998.35089263610526.467795501
 2314851.3825715610573.792562833 2314903.1342895610837.972658528
#Sta/Elev= 30
       0 3007.07    20.3 3003.21    41.6 3000.97    46.6 3000.02    51.9 2998.42
    56.5 2996.58    61.4 2996.12    71.3 2996.19    81.1 2997.09   177.72997.153
     196  2997.3   277.3 2997.13   305.8  2998.4     314 2998.02   322.1 2997.16
   330.3 2997.82   342.5 2996.46   362.9 2996.49   382.4 2997.09   397.5 2998.61
   411.8 2998.19   436.2 2998.85   452.5 3001.91   460.7  3005.1   469.1 3007.38
     477 3010.57   489.2 3016.37   497.4 3018.91   501.5 3020.66   506.3 3023.86
#Mann= 5 ,-1,0
       0     .06       0      70      .1       0   177.7    .045       0
     196      .1       0  417.13     .06       0
#XS Ineff= 1 ,-1
  303.71   496.4  3006.7
Permanent Ineff=
       F
Bank Sta=177.7,196
XS Rating Curve= 0 ,0
Exp/Cntr(USF)=0,0
Exp/Cntr=0.3,0.1

Type RM Length L Ch R = 1 ,566     ,54.2,48.4,44
XS GIS Cut Line= 6
2315043.53628177 610442.486249482315003.70599097610495.757135985
2314977.43040052610511.0375649582314861.62251658610557.609947239
2314842.72968766610569.679788868 2314900.9721986 610837.54662316
#Sta/Elev= 30
       0 3008.73    12.9 3005.53    32.3 3002.33    63.3 2999.71    77.3 2996.21
   132.8 2996.11   162.9 2993.26   176.4 2994.27   184.5 2994.01   189.1 2993.29
   199.1 2994.25   210.2 2996.67   220.6  2997.2   292.8 2997.13   309.1 2997.57
   318.9 2998.45   333.7 2997.08   342.5 2997.68   354.2 2996.37   362.6 2996.38
   382.8 2996.59   411.5 2998.86   420.4 2998.18   444.2 2998.49   464.7 3001.74
     477 3005.72   489.2 3010.34   501.5  3016.1   513.8 3020.28   518.3 3022.91
#Mann= 5 ,-1,0
       0     .06       0      60      .1       0   184.5    .045       0
   199.1      .1       0  424.15     .06       0
#XS Ineff= 2 , 0
          127.63 3004.32  317.47         3005.58
Permanent Ineff=
       F       F
Bank Sta=184.5,199.1
XS Rating Curve= 0 ,0
Exp/Cntr(USF)=0,0
Exp/Cntr=0.3,0.1

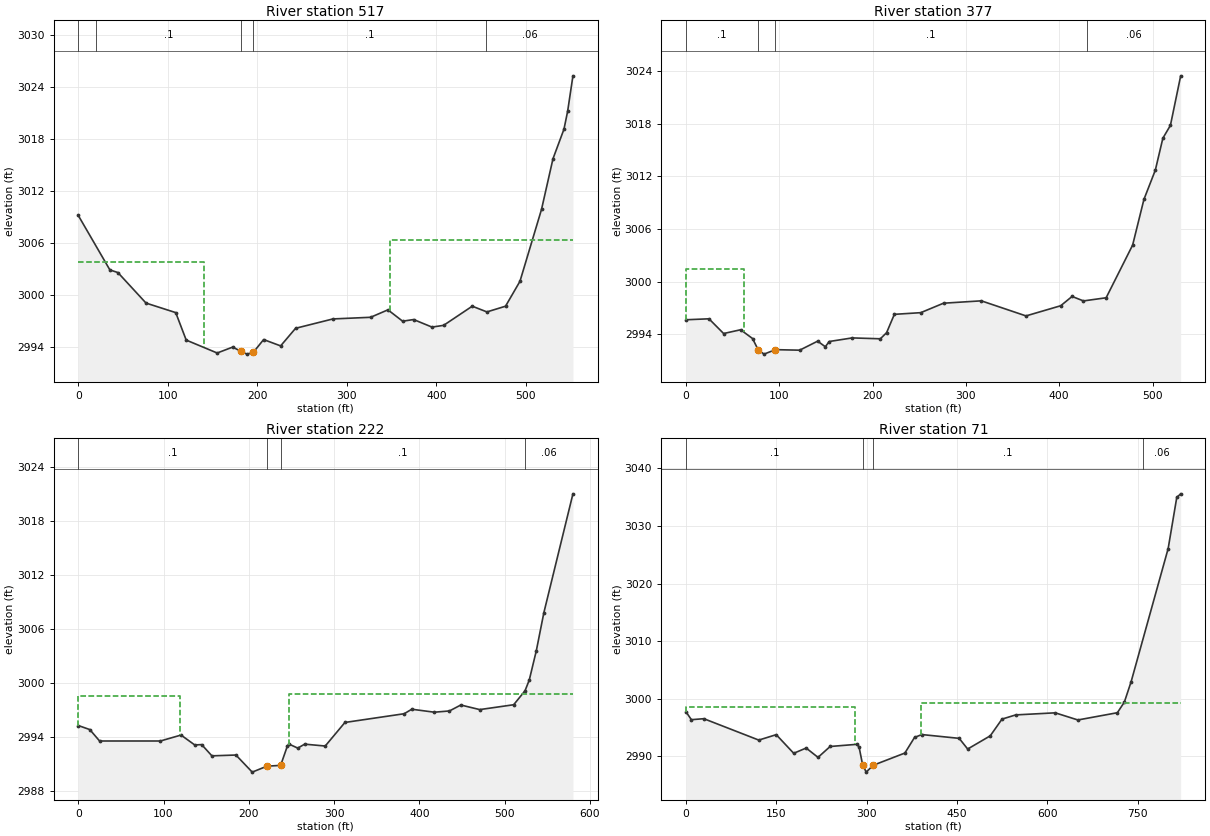
Type RM Length L Ch R = 1 ,517     ,155.5,140.3,127.6
XS GIS Cut Line= 4
2315019.57036785610392.8777774952314929.75639545 610438.82911221
2314829.49893789610543.2639638362314896.33724293610842.991988001
#Sta/Elev= 30
       0 3009.16    35.3 3002.88    44.3 3002.57    75.7 2999.05   108.9 2997.95
   120.6 2994.78   155.2 2993.29   172.5 2993.97   181.8 2993.48   188.5 2993.16
   195.6 2993.37   207.1 2994.84   226.1 2994.11   242.8 2996.14   284.5 2997.22
   326.6 2997.41     346 2998.27   362.4 2996.96   374.7 2997.15   395.2 2996.28
   408.2 2996.48   440.2 2998.69   456.6 2998.03   477.4 2998.69   493.5 3001.56
   517.6 3009.86   530.4  3015.7   542.7 3019.12   546.8 3021.19   552.7 3025.27
#Mann= 5 ,-1,0
       0     .06       0      20      .1       0   181.8    .045       0
   195.6      .1       0  455.66     .06       0
#XS Ineff= 2 , 0
          140.34 3003.78  347.83         3006.35
Permanent Ineff=
       F       F
Bank Sta=181.8,195.6
XS Rating Curve= 0 ,0
Exp/Cntr(USF)=0,0
Exp/Cntr=0.3,0.1

Type RM Length L Ch R = 1 ,377     ,90.3,155,157
XS GIS Cut Line= 4
2314807.80058578610329.5046184252314788.51219083610384.765147802
2314825.35424435610541.6359571532314875.79656907 610848.05773345
#Sta/Elev= 30
       0 2995.65    24.6 2995.76    40.3 2994.08    58.5 2994.51    71.3 2993.51
    77.32992.231    83.6 2991.73    95.9 2992.24   121.8 2992.18   141.1 2993.21
   149.3 2992.57   153.5 2993.17   178.1 2993.58   208.3 2993.48     215 2994.18
   223.3 2996.27   251.6 2996.46     276 2997.54   316.5 2997.81   364.4 2996.09
   401.6 2997.25   413.8 2998.31     426  2997.8   450.3 2998.16   478.7 3004.17
   490.8 3009.38     503 3012.71   511.1 3016.36   519.2 3017.83   530.2 3023.48
#Mann= 4 ,-1,0
       0      .1       0    77.3    .045       0    95.9      .1       0
  429.67     .06       0
#XS Ineff= 2 , 0
           61.84 3001.46
Permanent Ineff=
       F       F
Bank Sta=77.3,95.9
XS Rating Curve= 0 ,0
Exp/Cntr(USF)=0,0
Exp/Cntr=0.3,0.1

Type RM Length L Ch R = 1 ,222     ,205.9,150.8,148.2
XS GIS Cut Line= 4
2314793.66364019610326.869720034 2314740.1669835610381.339043212
2314714.80894113610597.1549234112314837.55971843610855.998953796
#Sta/Elev= 30
       0 2995.28    13.5 2994.83      25 2993.56    96.3 2993.56   120.5 2994.22
   136.6 2993.12   144.7 2993.16   156.7 2991.91   184.9    2992     204  2990.1
   221.2 2990.76   237.3 2990.85   245.3 2993.02   247.7 2993.19   257.4 2992.77
   265.5 2993.21   289.6    2993   312.7 2995.62   382.2 2996.59   391.1 2997.09
   417.6 2996.76   435.3  2996.9   448.6 2997.56   470.8 2997.05   510.6 2997.59
   523.9 2999.14   528.9 3000.34   537.2 3003.61     546 3007.82   580.1 3021.03
#Mann= 4 ,-1,0
       0      .1       0   221.2    .045       0   237.3      .1       0
  523.65     .06       0
#XS Ineff= 2 , 0
          118.84 2998.61  247.34         2998.73
Permanent Ineff=
       F       F
Bank Sta=221.2,237.3
XS Rating Curve= 0 ,0
Exp/Cntr(USF)=0,0
Exp/Cntr=0.3,0.1

Type RM Length L Ch R = 1 ,71      ,,,
XS GIS Cut Line= 4
2314860.77042617610291.926248796 2314649.2291296610349.252615588
2314635.54863838610568.9594357232314835.20744881610894.789079578
#Sta/Elev= 30
       0 2997.74     8.9 2996.38    29.6 2996.55   120.8 2992.84   149.8 2993.78
   178.8 2990.55   199.5 2991.46   219.2 2989.84   239.3 2991.73   283.2  2992.1
   287.2 2991.71   293.42988.486   299.3 2987.28   310.6 2988.46   363.4 2990.59
   379.4 2993.29   391.4  2993.8   453.6 2993.14   467.7 2991.29   505.2 2993.58
   524.7 2996.48   547.5 2997.21   613.1 2997.57   650.7 2996.33   716.3 2997.59
   727.9 2999.44   739.1 3002.97   800.6 3026.07   814.9 3034.95   821.4 3035.57
#Mann= 4 ,-1,0
       0      .1       0   293.4    .045       0   310.6      .1       0
   759.3     .06       0
#XS Ineff= 2 , 0
          280.19 2998.58  389.69         2999.22
Permanent Ineff=
       F       F
Bank Sta=293.4,310.6
XS Rating Curve= 0 ,0
Exp/Cntr(USF)=0,0
Exp/Cntr=0.3,0.1
LCMann Table=0

Chan Stop Cuts=-1
Use User Specified Reach Order=0
Composite Channel Slope=5